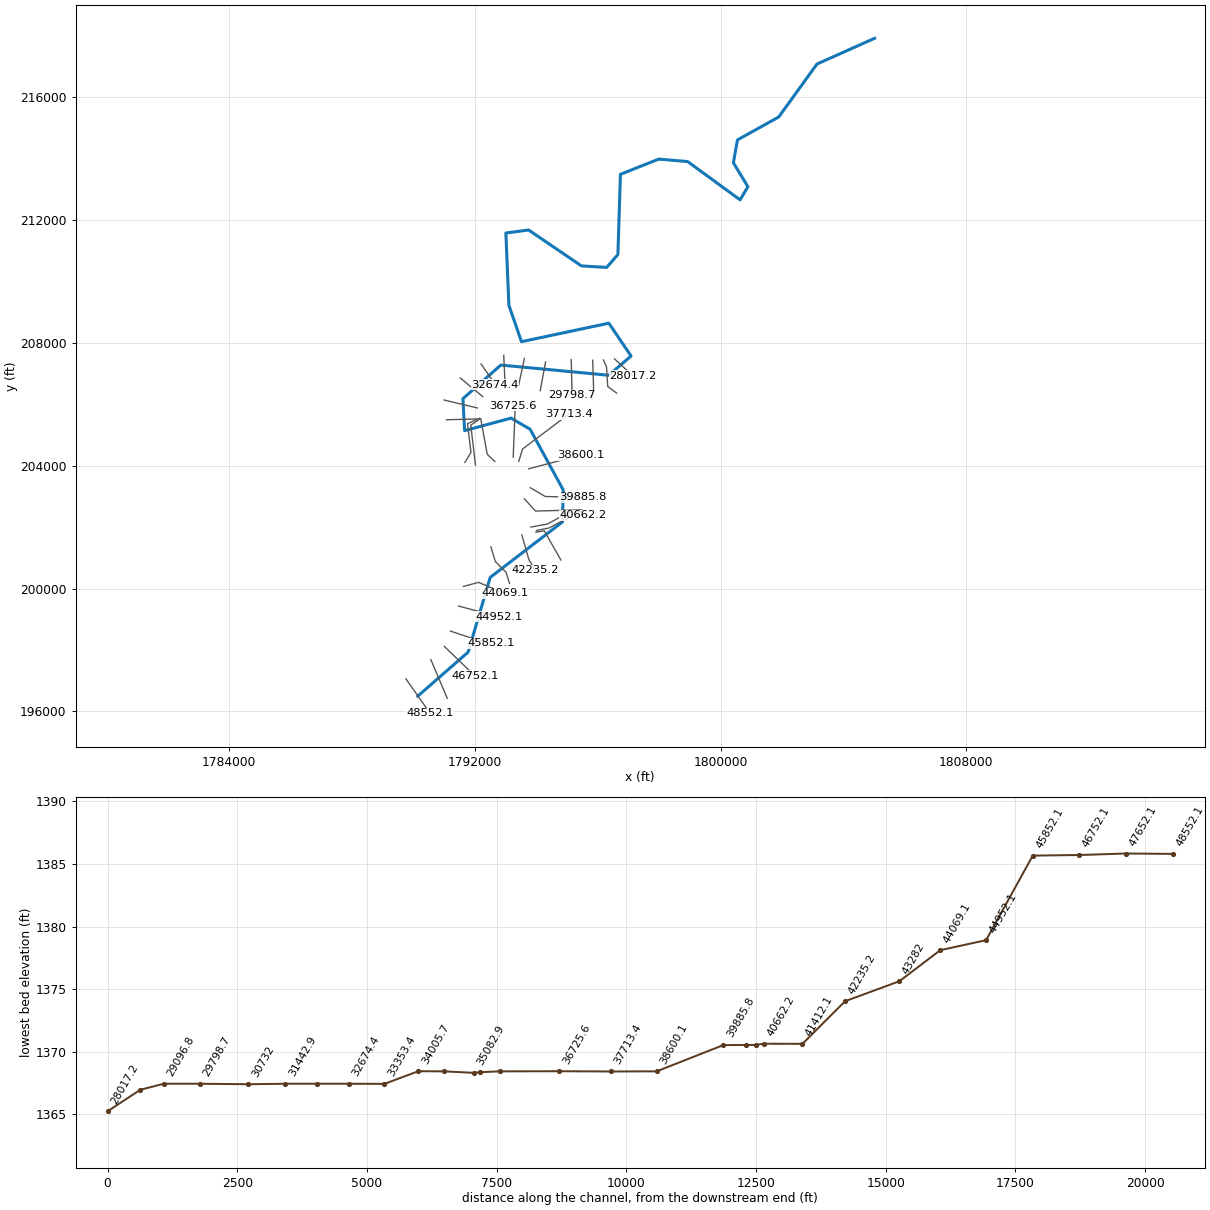
--- BUCKHANRV.prj (project) ---

Proj Title=BUCKHANRV
Current Plan=p01
Default Exp/Contr=0,0
English Units
Geom File=g01
Flow File=f01
Plan File=p01
BEGIN DESCRIPTION:
END DESCRIPTION:
DSS Export Rating Curves= 0
DSS Export Rating Curve Sorted= 0
DSS Export Volume Flow Curves= 0
DXF OffsetX= 0
DXF OffsetY= 0
DXF ScaleX= 0
DXF ScaleY= 0

--- BUCKHANRV.p01 (plan) ---

Plan Title=Floodplain
Program Version=4.00
Geom File=g01
Flow File=f01
K Sum by GR=0
Std Step Tol=0.01
Critical Tol=0.01
Num of Std Step Trials=20
Max Error Tol=0.3
Flow Tol Ratio=0.001
Split Flow NTrial=30
Split Flow Tol=0.02
Split Flow Ratio=0.02
Log Output Level=0
Friction Slope Method=1
Unsteady Friction Slope Method=2
Unsteady Bridges Friction Slope Method=1
Global Log Level=0
CheckData=False
Run HTab=0
Run UNet=0
Run PostProcess=0
UNET Theta=0
UNET Theta Warmup=0
UNET ZTol=0
UNET ZSATol=0
UNET MxIter=0
UNET MaxInSteps=0
UNET DtIC=0
UNET DtMin=0
UNET MaxCRTS=0
UNET WFStab=0
UNET SFStab=0
UNET WFX=0
UNET SFX=0
UNET DSS MLevel=0
UNET DZMax Abort=0
UNET Convert EG Bridges=0
UNET Use Existing IB Tables=0
UNET Froude Limit=0
UNET Froude Power=0
Write IC File=0
Echo Input=False
Echo Output=False
Write Detailed=0

--- BUCKHANRV.f01 (steady flow) ---

Flow Title=NFF Regression Equation
Program Version=5.03
Number of Profiles= 1
Profile Names=P100yr
River Rch & RM=BUCKHANRV,Main            ,48552.1
15284.03
River Rch & RM=BUCKHANRV,Main            ,35188
16519.71
River Rch & RM=BUCKHANRV,Main            ,532.2
17900.19
River Rch & RM=BUCKHANRV,Main            ,141.8
17901.03
Boundary for River Rch & Prof#=BUCKHANRV,Main            , 1
Up Type= 0
Dn Type= 3
Dn Slope=0.004171
DSS Import GetInterval= 0
DSS Import GetPeak= 0
DSS Import FillOption= 0

--- BUCKHANRV.g01 (geometry) ---

Geom Title=USGS 10m DEM
Program Version=4.10

River Reach=BUCKHANRV       ,Main
Reach XY= 30
     1790136.781      196497.997     1791779.149      197932.072
     1792497.679      200364.832     1794850.444      202168.976
     1794876.912      203211.545     1793796.186      205190.262
     1793177.533      205549.722     1791665.662      205142.772
     1791608.536      206183.707     1792844.035      207278.005
     1796356.401      206945.571     1797085.966      207572.596
     1796361.422      208640.661     1793516.277      208038.574
     1793106.368      209224.958     1793008.275      211576.502
     1793749.094      211674.621     1795467.803      210506.119
     1796290.487      210456.521     1796656.952      210875.269
     1796739.145      213487.388     1797988.146      213982.454
     1798928.426      213902.318     1800635.546      212656.296
     1800891.441      213082.055     1800418.336       213863.01
     1800550.117      214606.476     1801895.223      215353.982
     1803140.915      217078.106     1805015.796      217914.408

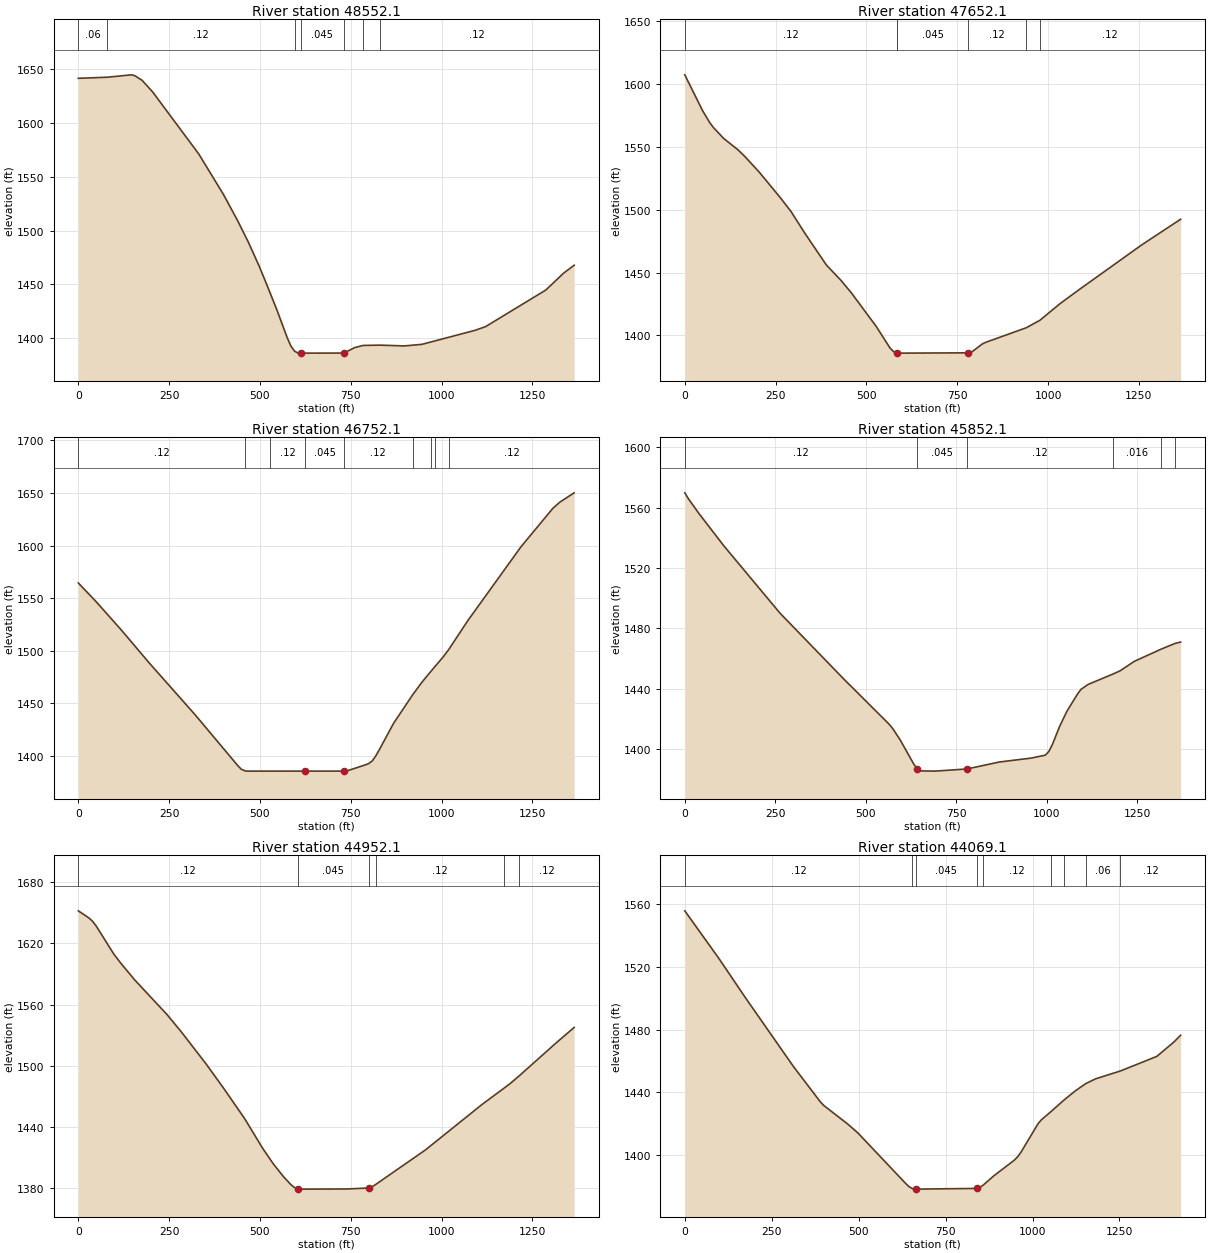
Type RM Length L Ch R = 1 ,48552.1 ,904.7,900,895.2
XS GIS Cut Line= 3
       1789752.2      197061.916     1790144.959      196503.752
     1790537.718      195945.589
#Sta/Elev= 30
       0 1641.73   80.291642.746   146.2 1644.97     156 1644.11   175.5 1639.86
   204.8 1628.96   331.5 1571.29   399.8 1533.42   438.8 1509.01     468 1489.23
   497.2 1467.32   516.8  1451.3     546 1426.65   575.2 1400.07     585 1392.55
   595.21387.682   604.5 1385.88   612.51385.822   614.2 1385.81   731.2 1385.86
   760.5 1390.92  783.951392.972  831.721393.245     897 1392.51   945.8 1393.98
    1092 1407.02  1121.2  1410.5    1287 1444.56  1335.8 1460.25    1365 1467.67
#Mann= 7 ,-1 , 0
       0     .06       0   80.29     .12       0   595.2     .04       0
   612.5    .045       0   731.2     .12       0  783.95    .016       0
  831.72     .12       0
Bank Sta=612.5,731.2
XS Rating Curve= 0 ,0
Exp/Cntr=0.3,0.1

Type RM Length L Ch R = 1 ,47652.1 ,890.9,900,909.1
XS GIS Cut Line= 3
     1790565.549      197685.885     1790832.655      197057.824
     1791099.761      196429.763
#Sta/Elev= 30
       0 1607.32    48.8 1578.91    68.2 1569.51      78 1565.66   107.2 1556.64
   146.2 1547.71   165.8 1542.19   204.8 1529.93   263.2 1509.48   292.5 1498.52
   331.5 1480.84     390  1455.9     429 1444.04   458.2 1433.93   526.5  1407.3
   565.5 1389.69   575.2 1387.02  584.861385.867     585 1385.85   594.8 1385.84
     780 1386.07   789.8 1386.66     819 1393.15   828.8 1394.47  940.541406.088
  977.611411.973  1033.5 1425.32  1082.2 1435.66  1257.8 1471.96    1365 1492.39
#Mann= 6 ,-1 , 0
       0     .12       0  584.86     .04       0     585    .045       0
     780     .12       0  940.54    .016       0  977.61     .12       0
Bank Sta=585,780
XS Rating Curve= 0 ,0
Exp/Cntr=0.3,0.1

Type RM Length L Ch R = 1 ,46752.1 ,889.6,900,911.1
XS GIS Cut Line= 3
     1791006.311      198114.556     1791498.574      197641.816
     1791990.837      197169.075
#Sta/Elev= 30
       0 1564.51    48.8 1546.82     117 1520.36     195 1488.61   321.8 1439.17
   438.8 1391.03   448.5 1387.55  459.731385.847     468 1385.72   528.2 1385.73
     624 1385.73   731.2 1385.74     741 1386.08   789.8 1391.64   799.5 1392.91
   809.2 1395.41     819 1400.22   828.8 1406.18   867.8 1431.12  920.411458.255
   945.8 1470.15  969.781480.185  982.791485.472  1004.2 1494.16  1019.91501.356
  1072.5 1528.85  1218.8 1598.99  1306.5 1635.49    1326 1641.42    1365 1650.18
#Mann= 9 ,-1 , 0
       0     .12       0  459.73     .04       0   528.2     .12       0
     624    .045       0   731.2     .12       0  920.41    .016       0
  969.78     .12       0  982.79    .016       0  1019.9     .12       0
Bank Sta=624,731.2
XS Rating Curve= 0 ,0
Exp/Cntr=0.3,0.1

Type RM Length L Ch R = 1 ,45852.1 ,898.6,900,899.9
XS GIS Cut Line= 3
     1791202.875      198617.499     1791849.385      198401.995
     1792513.467      198221.133
#Sta/Elev= 30
       0 1569.73     9.7 1565.91    38.9 1556.12   107.1 1534.91   262.9 1490.18
   438.1 1446.86   564.7 1416.66   574.4 1413.82   593.9 1406.77   632.8 1390.26
   642.5 1387.15   652.3 1385.82   691.3 1385.67   779.8  1387.1   868.3 1391.68
   956.8 1394.28   996.1 1396.24    1006 1398.77  1015.8 1403.44  1035.4 1415.14
  1055.1 1425.02  1084.6 1436.53  1094.4 1439.73  1114.1 1442.99  1183.61449.952
  1202.6 1452.02  1241.9 1458.27 1315.681466.313 1354.591470.141  1369.8 1471.03
#Mann= 6 ,-1 , 0
       0     .12       0   642.5    .045       0   779.8     .12       0
  1183.6    .016       0 1315.68     .12       0 1354.59    .016       0
Bank Sta=642.5,779.8
XS Rating Curve= 0 ,0
Exp/Cntr=0.3,0.1

Type RM Length L Ch R = 1 ,44952.1 ,886.2,883.1,880
XS GIS Cut Line= 3
     1791465.214      199432.894     1792124.315      199255.716
     1792783.417      199078.539
#Sta/Elev= 30
       0 1651.97    29.2 1644.97      39 1641.77    48.8 1637.29    97.5 1609.66
     117 1600.51     156 1583.87   243.8 1550.34   282.8 1533.54     351  1502.1
   399.8 1478.01   458.2 1447.92     507 1419.23   536.2 1403.96   565.5 1390.87
     585  1383.4   594.8 1380.51   604.5 1379.05   614.2 1378.91     741 1379.06
   799.5 1380.05   809.2 1381.27  819.411383.669   955.5 1417.34  1111.5    1462
 1172.47 1478.11  1189.5 1482.67 1213.581490.008  1316.2 1522.63    1365 1537.53
#Mann= 6 ,-1 , 0
       0     .12       0   604.5    .045       0   799.5     .04       0
  819.41     .12       0 1172.47    .016       0 1213.58     .12       0
Bank Sta=604.5,799.5
XS Rating Curve= 0 ,0
Exp/Cntr=0.3,0.1

Type RM Length L Ch R = 1 ,44069.1 ,795.8,787,778.3
XS GIS Cut Line= 3
     1791629.861      200072.798     1792120.313      200203.006
     1792966.126      199844.803
#Sta/Elev= 30
       0 1555.83    97.6 1525.57   175.6 1499.95   312.3 1456.46   390.3 1433.71
   400.1 1431.47   468.4 1419.71   497.7 1414.02   634.5 1381.91   644.2 1379.79
  654.371378.456   663.8 1378.11   839.7 1378.56   849.4 1379.28  858.06 1380.65
   888.5 1386.55   947.2 1396.51   956.9 1398.66   966.7 1401.61  1015.6 1419.75
  1025.3 1422.34 1053.191427.624 1090.071434.904  1123.1 1440.85 1152.891445.467
  1181.7 1448.57 1252.331453.523  1357.6 1462.88  1406.4    1472    1426 1476.36
#Mann= 9 ,-1 , 0
       0     .12       0  654.37     .04       0   663.8    .045       0
   839.7     .04       0  858.06     .12       0 1053.19    .016       0
 1090.07     .12       0 1152.89     .06       0 1252.33     .12       0
Bank Sta=663.8,839.7
XS Rating Curve= 0 ,0
Exp/Cntr=0.3,0.1

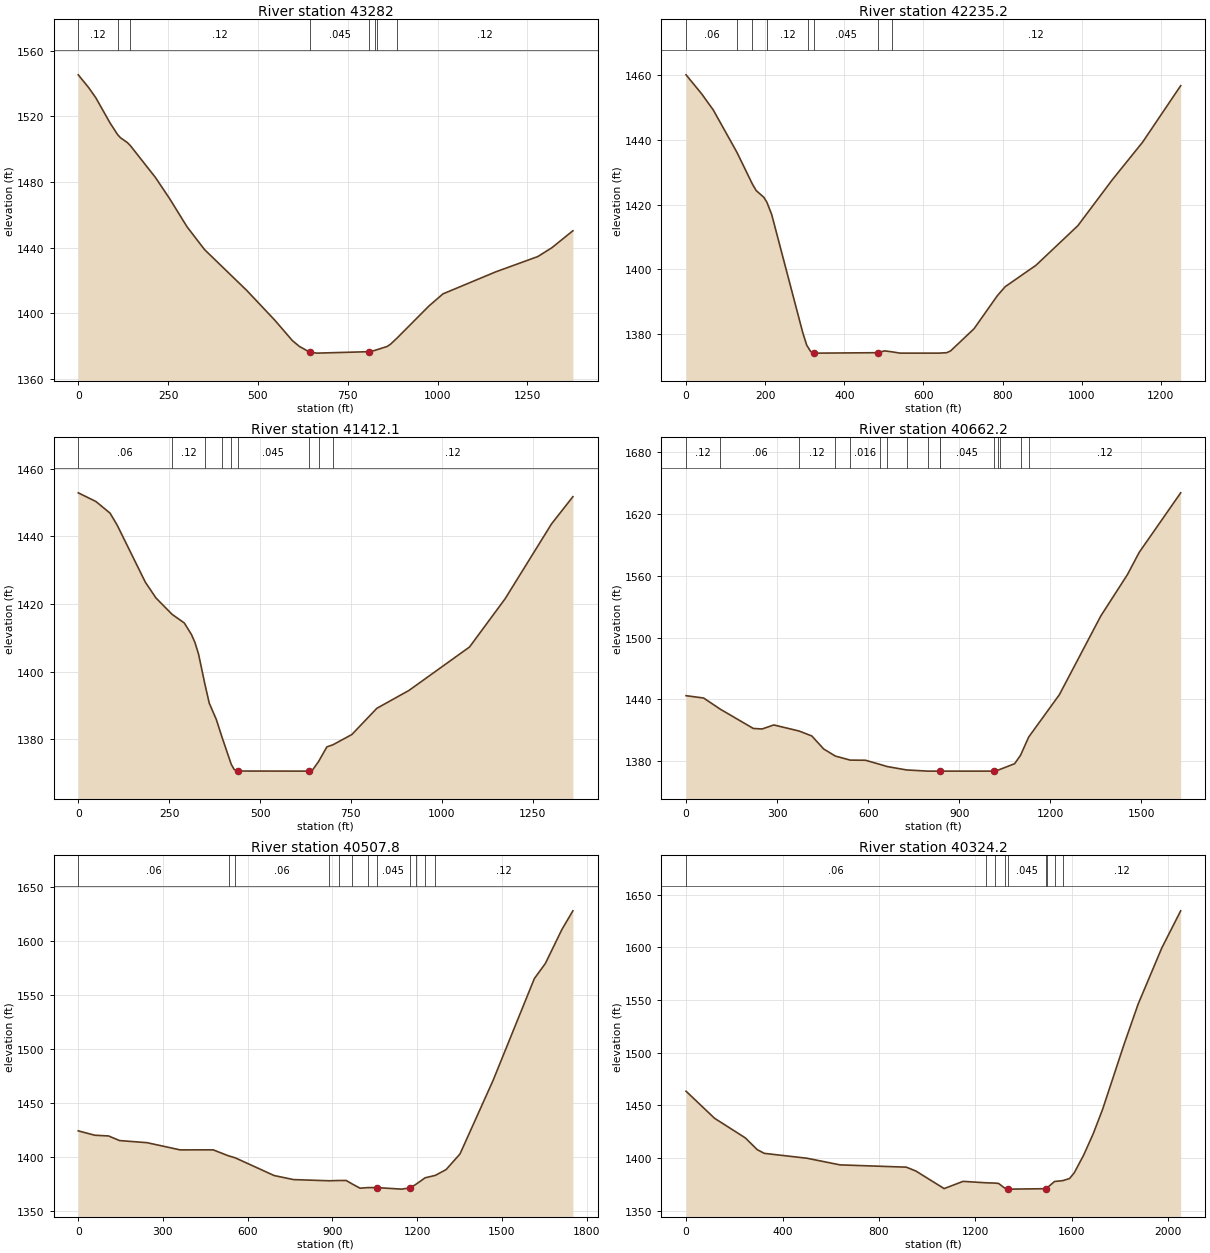
Type RM Length L Ch R = 1 ,43282   ,1058.2,1046.9,1035.5
XS GIS Cut Line= 4
     1792519.618       201361.86     1792662.848       200884.43
     1793013.708      200532.168     1793127.257      200168.284
#Sta/Elev= 30
       0  1545.4    29.3 1537.51    48.9 1531.38      88 1516.22  109.421508.948
   117.3 1507.05   136.8 1504.05  145.121502.182     215 1482.72   254.1 1469.94
     303 1452.62   351.8 1438.72   469.1 1413.85   547.2 1395.69   595.9  1383.3
   615.4 1379.74   644.7 1376.16   664.2 1375.63   810.4 1376.52  825.941377.324
  830.971377.692   859.2 1379.64   868.9 1381.02  887.821384.926   976.1 1404.38
  1015.2 1411.78  1161.8 1425.19  1279.1 1434.53  1318.2 1439.91  1376.8 1450.27
#Mann= 8 ,-1 , 0
       0     .12       0  109.42    .016       0  145.12     .12       0
   644.7    .045       0   810.4     .04       0  825.94     .12       0
  830.97    .016       0  887.82     .12       0
Bank Sta=644.7,810.4
XS Rating Curve= 0 ,0
Exp/Cntr=0.3,0.1

Type RM Length L Ch R = 1 ,42235.2 ,817.6,823.1,828.4
XS GIS Cut Line= 3
     1793526.563      201752.485     1793759.496      200939.202
     1793969.271      200593.631
#Sta/Elev= 30
       0 1460.15    39.4 1454.27    68.9 1449.25  128.731436.134   167.41426.408
   177.1 1424.36   196.7 1422.23  204.141420.772   216.4 1416.95   295.1 1380.31
     305 1376.49  308.69 1375.76   314.8 1374.55   324.6 1374.05   334.5 1374.03
   484.61374.164   501.7 1374.73   519.81374.443     541 1374.03   639.4 1374.03
   659.1 1374.17   668.9 1374.74   727.9 1381.58     787 1391.84   806.6 1394.59
   884.5 1401.22   990.4 1413.48    1077 1427.62    1154 1439.32  1250.2 1456.79
#Mann= 8 ,-1 , 0
       0     .06       0  128.73     .12       0   167.4    .016       0
  204.14     .12       0  308.69     .04       0   324.6    .045       0
   484.6    .016       0   519.8     .12       0
Bank Sta=324.6,484.6
XS Rating Curve= 0 ,0
Exp/Cntr=0.3,0.1

Type RM Length L Ch R = 1 ,41412.1 ,713.2,749.9,786.6
XS GIS Cut Line= 3
     1793990.973      201839.291      1794260.07      201878.353
     1794798.264      200932.173
#Sta/Elev= 30
       0 1452.87    48.6  1450.3    87.4 1446.87   106.8 1443.37   184.5 1426.46
   213.6 1421.81  258.211416.944   291.5 1414.42   311.1 1411.04     321 1408.62
   330.8 1405.22  348.391396.291   360.2 1390.73   379.8 1385.85  395.541380.594
  420.681372.659   428.8 1371.11   438.6 1370.65   634.8 1370.62   644.6    1371
  660.871373.451   683.8 1377.79  700.231378.393   752.4 1381.43   821.1 1389.18
   909.4 1394.46  1076.1  1407.3  1174.1 1421.58  1301.6 1443.68  1360.4 1451.73
#Mann= 9 ,-1 , 0
       0     .06       0  258.21     .12       0  348.39    .016       0
  395.54     .12       0  420.68     .04       0   438.6    .045       0
   634.8     .12       0  660.87    .016       0  700.23     .12       0
Bank Sta=438.6,634.8
XS Rating Curve= 0 ,0
Exp/Cntr=0.3,0.1

Type RM Length L Ch R = 1 ,40662.2 ,155.5,154.4,153.8
XS GIS Cut Line= 4
     1794003.993      201891.374     1794419.581      201975.829
     1795128.125      202360.124     1795527.431      202381.826
#Sta/Elev= 30
       0 1443.69    57.8 1441.44  113.031430.569   221.7 1411.95   250.6 1411.44
   289.2 1415.34  372.66 1409.46   414.4 1404.68   453.6 1392.08  491.941385.207
  541.221381.289   591.2 1381.16  639.92 1377.08  662.571375.082  726.451371.773
  797.141370.631   797.6 1370.63  836.76 1370.63   836.9 1370.63  1013.9 1370.64
 1027.071371.478 1034.521372.307  1082.7 1377.81 1102.341386.038 1128.881403.521
  1230.1  1444.6  1366.7 1520.86  1454.5 1560.95  1493.5 1582.58    1630 1640.14
#Mann= 16 ,-1 , 0
       0     .12       0  113.03     .06       0  372.66     .12       0
  491.94     .08       0  541.22    .016       0  639.92     .06       0
  662.57     .12       0  726.45     .06       0  797.14     .12       0
  836.76     .04       0   836.9    .045       0  1013.9     .04       0
 1027.07     .08       0 1034.52    .016       0 1102.34     .08       0
 1128.88     .12       0
Bank Sta=836.9,1013.9
XS Rating Curve= 0 ,0
Exp/Cntr=0.3,0.1

Type RM Length L Ch R = 1 ,40507.8 ,194.6,183.5,171.8
XS GIS Cut Line= 4
     1793821.702      202004.221     1794358.817      202101.697
     1795067.361      202485.992     1795466.667      202507.694
#Sta/Elev= 30
       0 1424.38    58.5 1420.32   107.2 1419.66   146.2  1415.4   243.7 1413.44
   360.7  1406.8   477.6 1406.83  532.141401.291  555.721399.478   693.3 1383.12
   762.2 1379.34  889.361378.241  923.271378.507   948.9 1378.52  969.541375.384
   998.1 1371.38    10251371.931    1057 1371.95  1145.5 1370.53    1175 1371.66
 1194.561374.737 1228.471380.986    1265 1383.28  1302.8  1388.6  1351.9    1403
    1469 1470.91  1615.3 1565.07  1654.3 1579.02  1712.8  1610.4  1751.8 1627.67
#Mann= 12 ,-1 , 0
       0     .06       0  532.14     .12       0  555.72     .06       0
  889.36     .08       0  923.27    .016       0  969.54     .12       0
    1025     .08       0    1057    .045       0    1175     .04       0
 1194.56     .08       0 1228.47    .016       0    1265     .12       0
Bank Sta=1057,1175
XS Rating Curve= 0 ,0
Exp/Cntr=0.3,0.1

Type RM Length L Ch R = 1 ,40324.2 ,439.5,438.4,437.3
XS GIS Cut Line= 3
     1793609.028       202924.36     1793973.611      202525.055
     1795484.028      202564.117
#Sta/Elev= 30
       0  1463.4     118 1437.78   245.8 1419.13   294.9 1408.03   324.4 1404.47
   501.4 1399.83   638.8 1393.53   913.5 1391.37   952.8 1387.75  1070.5 1371.04
    1149 1377.89 1242.691376.559 1279.991376.274  1296.2 1375.94 1321.361371.554
  1335.4 1370.54  1345.2 1370.53  1492.4 1370.94 1498.741371.994  1528.31377.764
 1563.011378.604  1590.5 1380.58  1610.1    1386  1649.4 1402.94  1688.6 1422.93
  1727.9 1446.34  1816.2 1507.53    1875 1545.98  1973.1 1599.24  2051.6 1634.53
#Mann= 9 ,-1 , 0
       0     .06       0 1242.69     .12       0 1279.99    .016       0
 1321.36     .08       0  1335.4    .045       0  1492.4     .04       0
 1498.74     .08       0  1528.3    .016       0 1563.01     .12       0
Bank Sta=1335.4,1492.4
XS Rating Curve= 0 ,0
Exp/Cntr=0.3,0.1

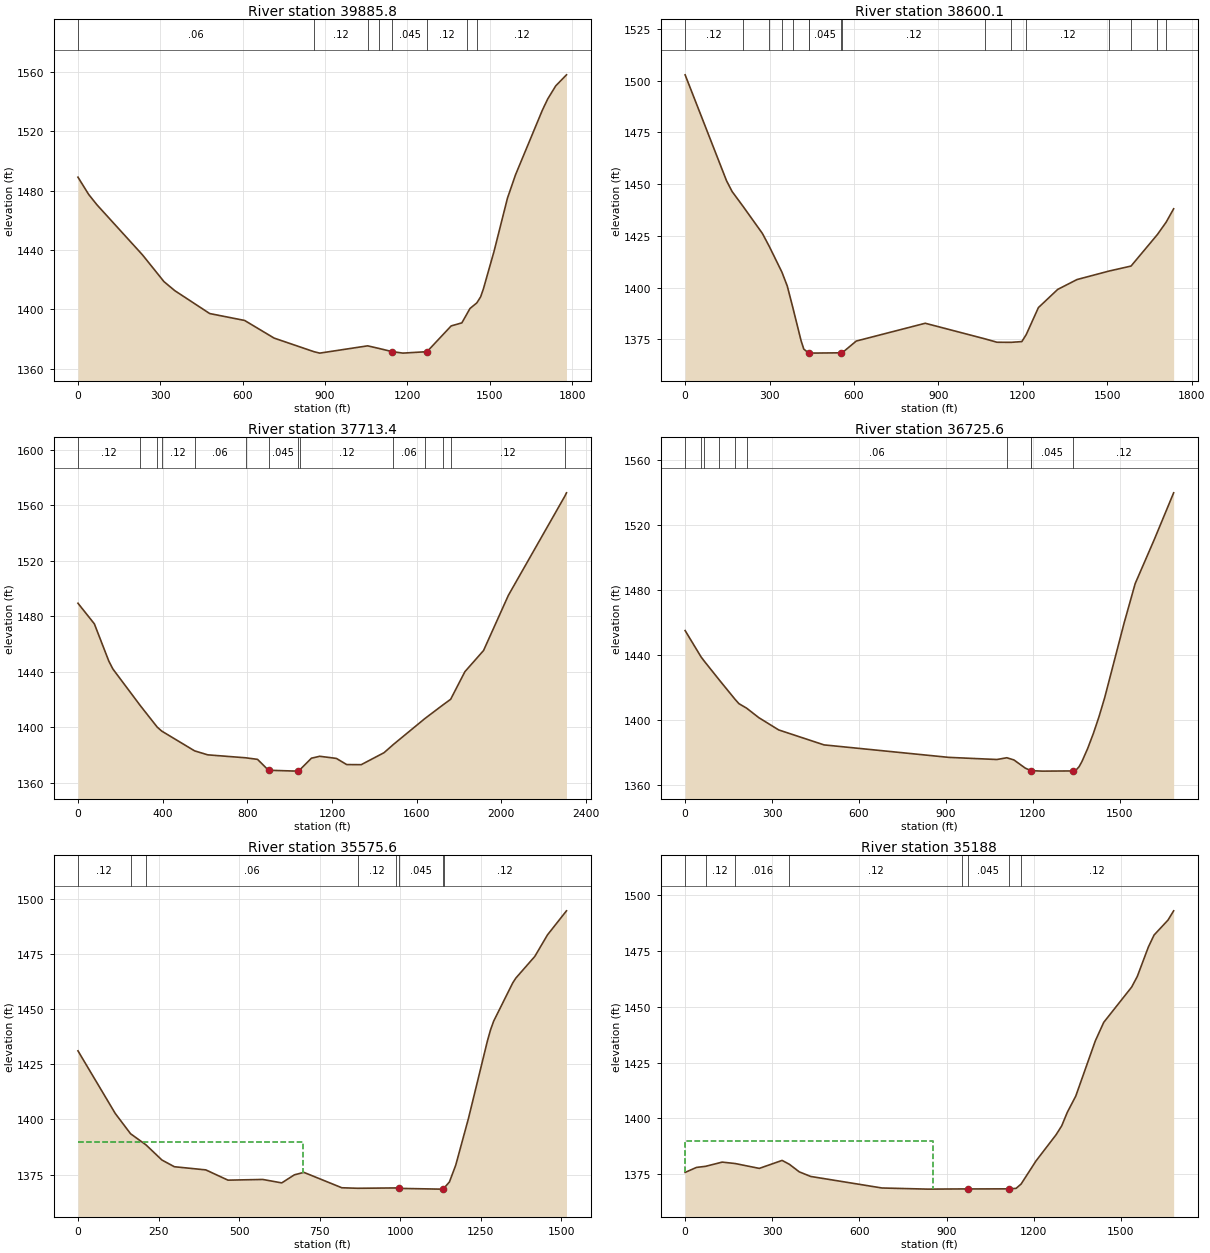
Type RM Length L Ch R = 1 ,39885.8 ,1279.4,1285.8,1292.1
XS GIS Cut Line= 3
      1793802.17      203284.603     1794292.622      202998.145
     1795503.559      202972.103
#Sta/Elev= 30
       0 1488.98    39.2 1477.32    68.6  1470.5     235 1436.68   313.4 1418.63
   352.5  1412.6   479.8 1397.17     607 1392.52   714.5 1380.63  858.911371.526
   880.6 1370.52 1054.991375.426 1095.881373.689  1144.3 1371.53  1183.4 1370.53
  1271.3  1371.5  1359.2 1388.83  1398.2  1390.9 1418.191397.439  1427.6 1400.54
 1452.741404.364  1466.6 1408.43  1476.4 1413.64  1515.5 1439.12  1564.3 1474.88
  1593.6 1490.58  1691.3 1534.06  1710.8 1541.63  1740.1 1550.48  1779.2  1557.9
#Mann= 8 ,-1 , 0
       0     .06       0  858.91     .12       0 1054.99    .016       0
 1095.88     .04       0  1144.3    .045       0  1271.3     .12       0
 1418.19    .016       0 1452.74     .12       0
Bank Sta=1144.3,1271.3
XS Rating Curve= 0 ,0
Exp/Cntr=0.3,0.1

Type RM Length L Ch R = 1 ,38600.1 ,877.9,886.7,895.5
XS GIS Cut Line= 2
     1793750.087      203900.923     1795429.775      204339.291
#Sta/Elev= 30
       0 1502.78   147.1 1451.66   166.7 1446.49  205.12 1439.41   274.6  1426.2
  299.26 1419.89  343.79 1407.57   362.9 1400.85  382.631390.488   411.9 1374.48
   421.7 1370.36  439.131368.464   441.3 1368.42   554.91368.574  558.791368.665
   608.1 1374.25   853.3 1382.84 1066.891375.258  1108.3 1373.67 1158.48 1373.63
  1196.5 1373.99 1212.021377.333  1255.4  1390.4    1324 1399.18  1392.7 1403.95
 1507.441408.077 1584.591410.449  1678.41425.703  1709.31431.627    1736  1438.1
#Mann= 16 ,-1 , 0
       0     .12       0  205.12     .06       0  299.26     .12       0
  343.79    .016       0  382.63     .12       0  439.13     .04       0
   441.3    .045       0   554.9     .04       0  558.79     .12       0
 1066.89     .07       0 1158.48     .04       0 1212.02     .12       0
 1507.44     .06       0 1584.59     .12       0  1678.4     .06       0
  1709.3     .12       0
Bank Sta=441.3,554.9
XS Rating Curve= 0 ,0
Exp/Cntr=0.3,0.1

Type RM Length L Ch R = 1 ,37713.4 ,967.8,987.8,1007.8
XS GIS Cut Line= 3
     1793428.907      204143.978     1793550.434      204543.284
     1795060.851      205680.437
#Sta/Elev= 30
       0 1489.38    77.6 1474.49   145.6 1447.75     165    1442  294.311415.655
  374.541400.111  395.761397.259  550.861383.022   613.3 1380.14  792.981378.009
   848.4 1376.89   900.21369.039  1034.5 1368.41  1040.2 1368.66 1048.341369.364
  1103.1 1377.73  1142.3 1379.11  1220.7 1377.58  1269.6 1373.14  1338.2 1373.06
    1446 1381.68 1490.431387.639 1639.391406.328 1724.041416.078 1760.751420.157
    1828 1440.04  1916.2 1455.31  2033.7 1495.13 2300.69 1566.63    2308 1568.92
#Mann= 14 ,-1 , 0
       0     .12       0  294.31     .06       0  374.54    .016       0
  395.76     .12       0  550.86     .06       0  792.98     .12       0
   900.2    .045       0  1040.2     .04       0 1048.34     .12       0
 1490.43     .06       0 1639.39     .12       0 1724.04     .06       0
 1760.75     .12       0 2300.69    .016       0
Bank Sta=900.2,1040.2
XS Rating Curve= 0 ,0
Exp/Cntr=0.3,0.1

Type RM Length L Ch R = 1 ,36725.6 ,1144.8,1150,1155
XS GIS Cut Line= 3
     1793246.615      204282.867     1793307.379      205758.562
     1793246.615      205958.214
#Sta/Elev= 30
       0 1454.95   54.951438.742   65.141436.337  118.081424.495  173.49 1412.37
   185.8 1409.94  211.99 1407.21   254.3 1401.34   322.8 1393.79   479.3 1384.58
   909.6  1376.9  1075.9 1375.58 1109.991376.669  1134.6 1375.31  1173.7 1370.27
 1192.911368.751  1193.3 1368.73  1232.4 1368.43    1340 1368.55  1349.8 1369.25
  1359.6 1371.23  1369.4 1374.41  1388.9 1382.35  1408.5 1391.55    1428 1401.91
  1447.6 1413.61  1514.9 1459.72  1552.8 1483.82  1619.2 1511.15  1685.6 1539.74
#Mann= 10 ,-1 , 0
       0     .12       0   54.95     .06       0   65.14     .12       0
  118.08     .06       0  173.49    .016       0  211.99     .06       0
 1109.99     .12       0 1192.91     .04       0  1193.3    .045       0
    1340     .12       0
Bank Sta=1193.3,1340
XS Rating Curve= 0 ,0
Exp/Cntr=0.3,0.1

Type RM Length L Ch R = 1 ,35575.6 ,388.7,387.6,386.6
XS GIS Cut Line= 3
     1792649.827      204139.638     1792402.431      204369.673
     1792189.757      205528.527
#Sta/Elev= 30
       0 1431.09   115.8  1402.7  163.281393.519   210.91388.506   260.6 1381.61
   299.2 1378.57   396.7 1377.14   465.5 1372.49   573.5  1372.8   632.4 1371.25
   671.6  1374.9   701.1 1376.01   818.9 1369.04  868.431368.803  986.991368.962
   995.6 1368.76  1123.3 1368.42  1133.1 1368.63 1136.441368.954  1152.7 1371.66
  1172.4 1379.31  1211.6 1400.34  1270.6 1435.56  1280.4 1440.65  1290.2 1444.61
  1349.1 1461.86  1358.9 1464.08  1417.8 1473.91  1457.1 1483.67    1516 1494.56
#Mann= 8 ,-1 , 0
       0     .12       0  163.28    .016       0   210.9     .06       0
  868.43     .12       0  986.99     .04       0   995.6    .045       0
  1133.1     .04       0 1136.44     .12       0
#XS Ineff= 2 , 0
          698.45 1389.56
Permanent Ineff=
       F       F
Bank Sta=995.6,1133.1
XS Rating Curve= 0 ,0
Exp/Cntr=0.3,0.1

Type RM Length L Ch R = 1 ,35188   ,105.1,105.1,105.1
XS GIS Cut Line= 3
     1792017.795      204025.749     1791864.217      205322.632
      1792176.65      205530.957
#Sta/Elev= 30
       0 1375.84    39.3 1378.08   70.471378.566   127.6 1380.45   171.91379.817
   255.3 1377.64   333.8 1381.21  358.951379.468   392.8 1376.09     432 1374.03
   677.5 1368.86   834.6 1368.35  953.331368.439   973.9 1368.43  1113.91368.476
    1139 1368.68 1156.45 1370.63  1207.8 1380.99  1276.5 1392.64  1296.1 1396.66
  1315.6  1402.8  1344.5 1409.99  1411.9 1434.74  1440.8 1443.03    1537 1458.86
  1556.3 1463.58  1594.8 1476.88  1614.1 1482.15  1662.2 1488.87  1681.5    1493
#Mann= 8 ,-1 , 0
       0     .06       0   70.47     .12       0   171.9    .016       0
  358.95     .12       0  953.33     .08       0   973.9    .045       0
  1113.9     .04       0 1156.45     .12       0
#XS Ineff= 2 , 0
          854.49 1390.03
Permanent Ineff=
       F       F
Bank Sta=973.9,1113.9
XS Rating Curve= 0 ,0
Exp/Cntr=0.3,0.1

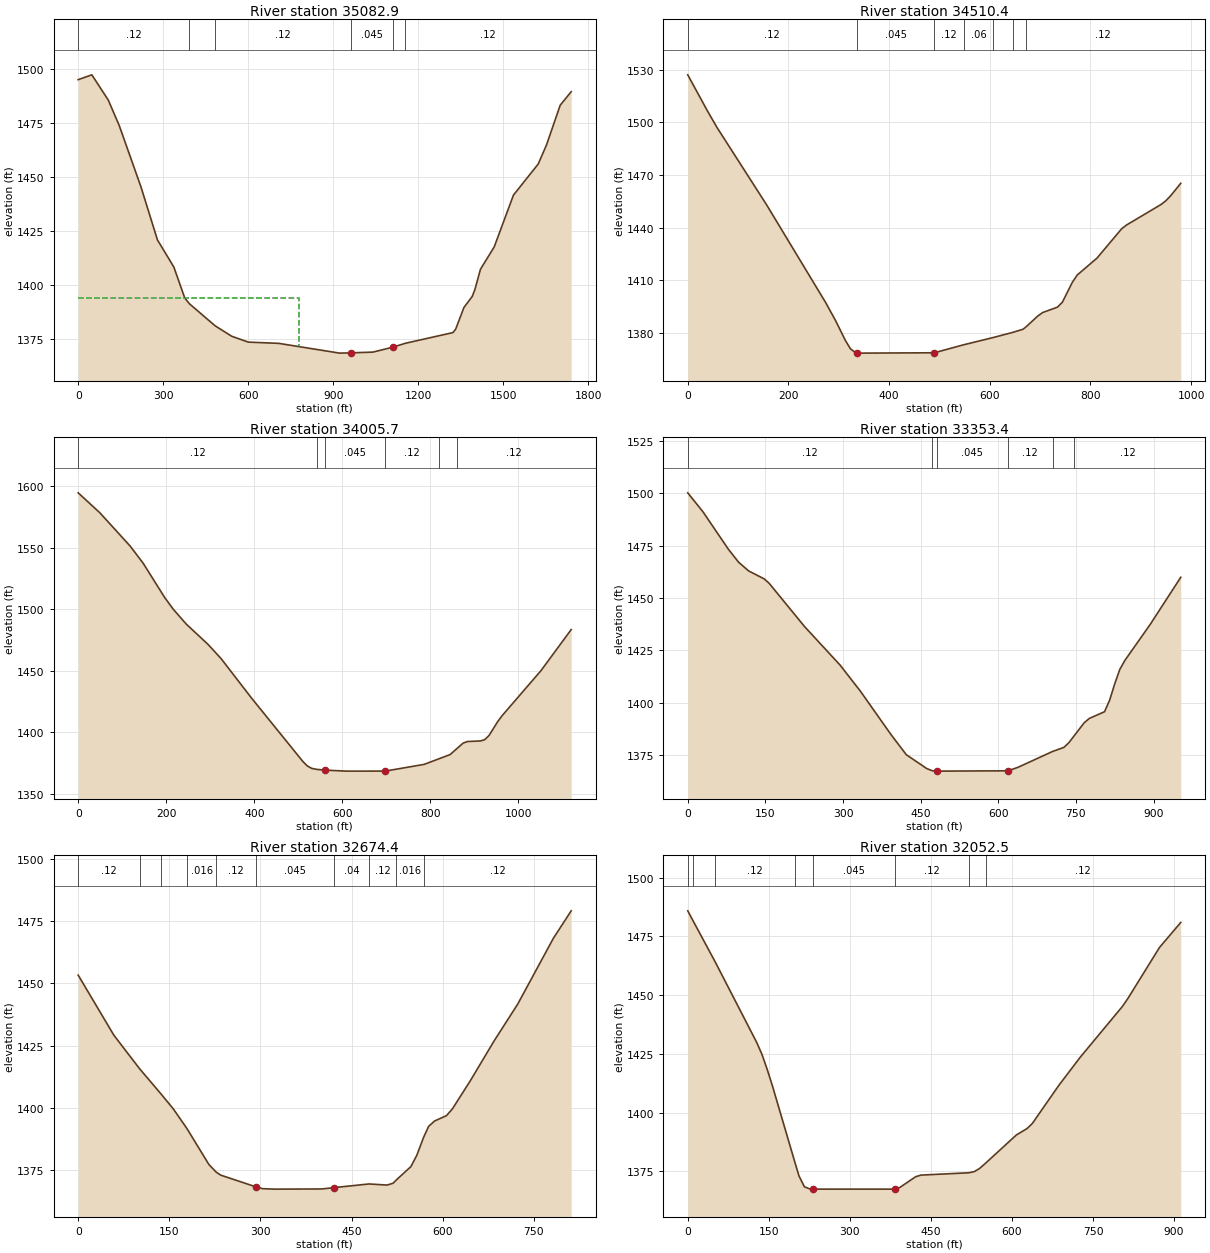
Type RM Length L Ch R = 1 ,35082.9 ,610.5,572.5,534.5
XS GIS Cut Line= 4
     1791674.045      204109.082     1791870.894      204429.576
     1791759.983      205369.499     1792140.191      205541.374
#Sta/Elev= 30
       0 1494.97    48.2 1497.21   106.1 1485.54   144.7 1473.77   221.8 1445.21
   279.7 1420.74   337.5  1408.2   376.1 1393.83  392.161391.206  483.051380.971
     542  1376.1   600.5  1373.4   707.9 1372.82   922.5  1368.3   961.6 1368.43
  1039.6 1368.76  1109.51371.017 1154.031372.841  1322.6 1377.82  1332.3 1379.47
  1361.4 1389.48  1390.5 1394.54  1400.2 1397.85  1419.6 1407.15  1468.1  1417.5
    1536 1441.49  1623.4  1455.9  1652.5 1464.69    1701 1483.14  1739.8 1489.41
#Mann= 6 ,-1 , 0
       0     .12       0  392.16    .016       0  483.05     .12       0
   961.6    .045       0  1109.5     .04       0 1154.03     .12       0
#XS Ineff= 2 , 0
          780.19 1394.05
Permanent Ineff=
       F       F
Bank Sta=961.6,1109.5
XS Rating Curve= 0 ,0
Exp/Cntr=0.3,0.1

Type RM Length L Ch R = 1 ,34510.4 ,510.6,504.7,498.8
XS GIS Cut Line= 2
     1791077.691      205497.103     1792056.858      205523.145
#Sta/Elev= 30
       0 1527.08    39.2 1506.46    58.8 1496.76   156.7 1452.96   274.3  1397.1
   293.8 1386.91   313.4 1375.54   323.2  1370.9     333 1368.77   335.71368.674
   342.8 1368.42   489.8 1368.62  548.64 1373.21  606.291377.264   645.71380.245
   666.1 1382.03  671.591383.257   695.4 1389.57   705.2 1391.57   734.6 1394.64
   744.4  1397.5     764 1408.73   773.8 1412.95     813 1422.57     862 1439.29
   871.8 1441.47   940.3 1453.15   950.1 1455.34   959.9 1458.31   979.5 1465.25
#Mann= 7 ,-1 , 0
       0     .12       0   335.7    .045       0   489.8     .12       0
  548.64     .06       0  606.29     .12       0   645.7    .016       0
  671.59     .12       0
Bank Sta=335.7,489.8
XS Rating Curve= 0 ,0
Exp/Cntr=0.3,0.1

Type RM Length L Ch R = 1 ,34005.7 ,662.6,652.2,641.8
XS GIS Cut Line= 2
     1790994.011      206140.506      1792083.42      205880.089
#Sta/Elev= 30
       0 1594.56    49.1  1578.4   117.9 1551.37   147.4 1537.47   196.5 1509.51
   216.2 1499.88   245.6 1487.88   294.8 1471.48   324.2 1460.06     393 1428.17
   510.9 1376.07   520.8 1372.57   530.6 1370.66  542.621369.828     560 1369.26
   609.2 1368.43   697.6 1368.46     786 1373.91  819.311378.414     845 1381.89
  859.54 1386.46   874.5 1391.19   884.3 1392.48   913.8 1392.95   923.6 1393.99
   933.4  1397.4   953.1 1408.63   962.9 1413.38  1051.3 1450.02  1120.1 1483.46
#Mann= 6 ,-1 , 0
       0     .12       0  542.62     .04       0     560    .045       0
   697.6     .12       0  819.31    .016       0  859.54     .12       0
Bank Sta=560,697.6
XS Rating Curve= 0 ,0
Exp/Cntr=0.3,0.1

Type RM Length L Ch R = 1 ,33353.4 ,685.2,679,672.7
XS GIS Cut Line= 2
     1791523.525      206856.652     1792257.032      206249.013
#Sta/Elev= 30
       0 1500.17    29.5 1491.08    78.6 1473.24    98.2 1467.09   117.8 1462.89
   147.3 1459.18   157.1 1457.06   225.8 1436.34   294.6 1417.93   333.9 1405.44
   392.8 1384.82   422.2 1375.27   461.5 1368.68  472.071367.623   481.2 1367.42
   618.6 1367.57   638.3 1369.26  705.011376.813   726.6 1378.73   736.5 1381.03
  746.82 1384.36   765.9 1390.49   775.8 1392.55   805.2 1395.75     815  1401.2
   824.8 1408.97   834.7 1415.93   844.5 1420.23   893.6 1437.45   952.5 1459.88
#Mann= 6 ,-1 , 0
       0     .12       0  472.07     .04       0   481.2    .045       0
   618.6     .12       0  705.01    .016       0  746.82     .12       0
Bank Sta=481.2,618.6
XS Rating Curve= 0 ,0
Exp/Cntr=0.3,0.1

Type RM Length L Ch R = 1 ,32674.4 ,634.5,621.9,609.3
XS GIS Cut Line= 2
     1792200.608      207312.381     1792660.677      206643.978
#Sta/Elev= 30
       0 1453.34    58.7 1429.24   100.91415.811  136.161405.684   156.4 1399.69
   179.11391.708   215.1 1377.33  227.331374.212   234.6 1373.05   293.3 1368.28
   303.1 1367.62   322.6 1367.43   400.8 1367.49   420.4 1368.02  478.741369.505
   508.4 1369.06   518.2  1369.8  523.861371.171   547.5 1376.46   557.2 1380.96
   568.51388.237   576.8 1392.65   586.6 1394.79   606.1 1396.93   615.9 1399.65
   645.2 1410.87   684.3 1426.85   723.4 1441.72   782.1 1468.15   811.4 1479.16
#Mann= 10 ,-1 , 0
       0     .12       0   100.9    .016       0  136.16     .12       0
   179.1    .016       0  227.33     .12       0   293.3    .045       0
   420.4     .04       0  478.74     .12       0  523.86    .016       0
   568.5     .12       0
Bank Sta=293.3,420.4
XS Rating Curve= 0 ,0
Exp/Cntr=0.3,0.1

Type RM Length L Ch R = 1 ,32052.5 ,615.5,609.6,603.8
XS GIS Cut Line= 2
     1792938.455      207594.499     1792981.858      206683.041
#Sta/Elev= 30
       0 1485.91    9.921481.628    51.31463.953   127.6  1429.9   137.4 1424.77
   147.2  1418.3     157 1411.19  198.981378.331     206 1372.98   215.9 1368.44
   225.7 1367.52   231.61367.472   245.3 1367.43   382.7 1367.43   392.5 1368.14
   421.9 1372.72   431.7  1373.4  519.631374.381   529.8 1374.83   539.6 1376.13
  551.511378.529   608.3  1390.5     628 1393.21   637.8 1395.39   686.8  1411.6
   726.1 1423.49   804.6 1445.23   814.4 1448.51   873.2 1470.33   912.5 1480.97
#Mann= 8 ,-1 , 0
       0     .12       0    9.92    .016       0    51.3     .12       0
  198.98     .04       0   231.6    .045       0   382.7     .12       0
  519.63    .016       0  551.51     .12       0
Bank Sta=231.6,382.7
XS Rating Curve= 0 ,0
Exp/Cntr=0.3,0.1

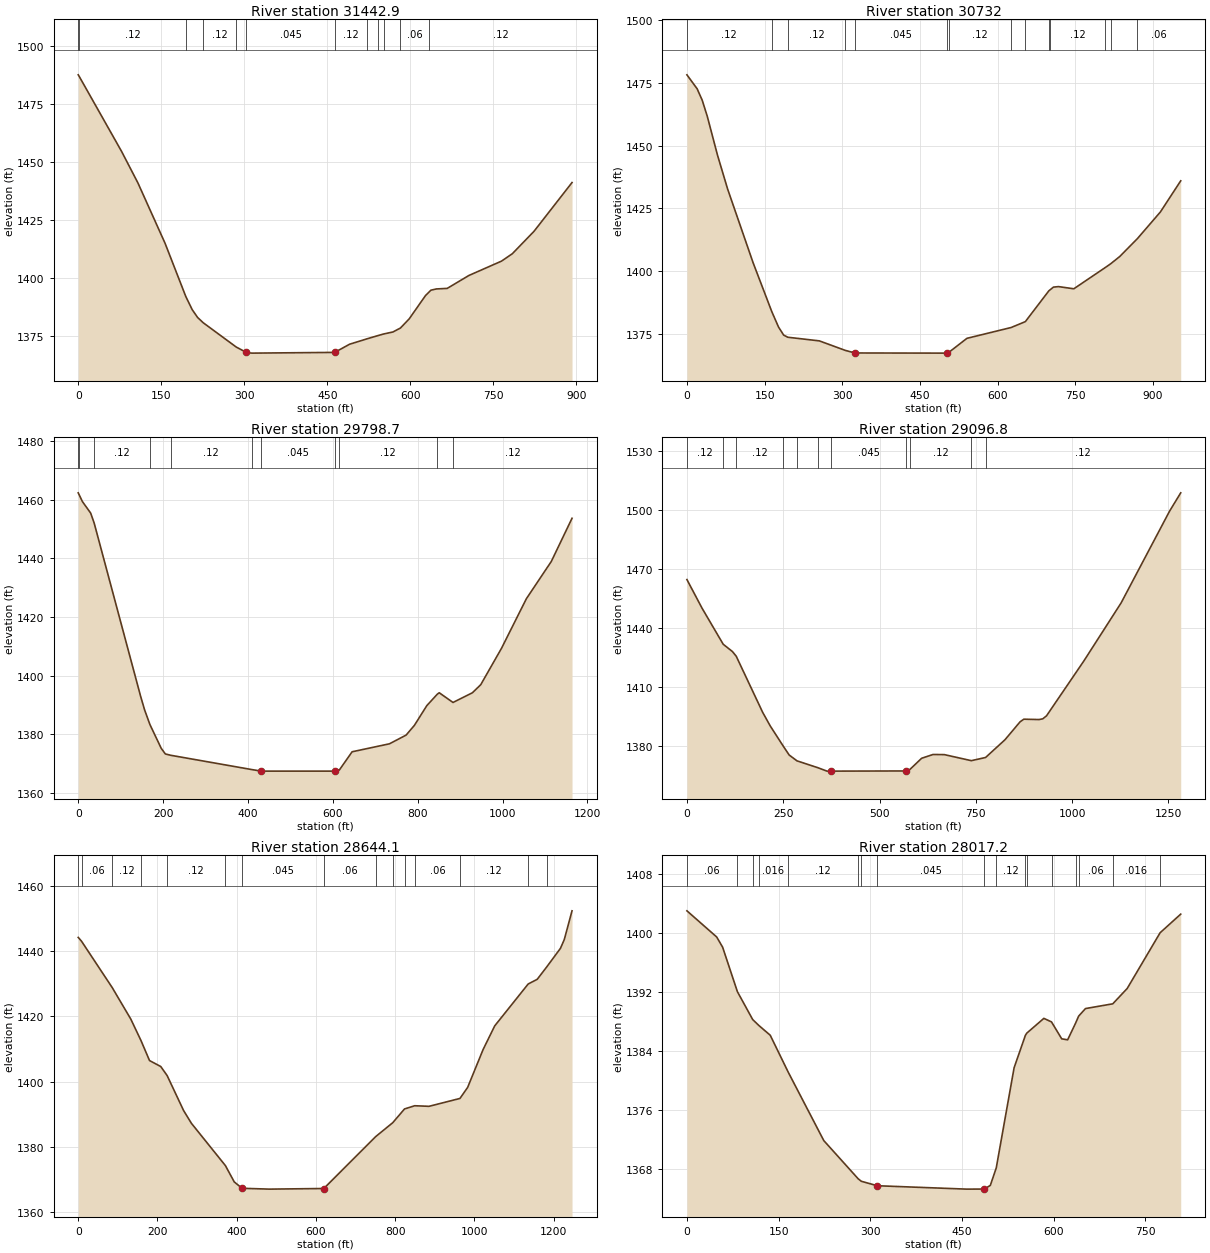
Type RM Length L Ch R = 1 ,31442.9 ,710.3,710.9,711.5
XS GIS Cut Line= 2
     1793611.198      207494.673     1793424.566      206622.277
#Sta/Elev= 30
       0 1487.37    1.541486.787    78.4 1454.33   107.8  1440.8   156.9 1414.76
  194.331391.839   205.9 1386.17   215.7 1382.79  225.751380.536  285.571370.032
   303.9 1367.73   313.7 1367.43   463.41367.746   490.2 1371.26   521.91373.604
  541.36 1374.98  551.651375.672   568.6 1376.55   582.11378.248     598 1382.22
   627.4 1392.24  633.841393.765   637.2 1394.56     647 1395.09   666.6 1395.33
   705.9 1400.91   764.7 1407.08   784.3 1410.28   823.5 1419.95   892.1 1440.95
#Mann= 12 ,-1 , 0
       0    .016       0    1.54     .12       0  194.33    .016       0
  225.75     .12       0  285.57     .04       0   303.9    .045       0
   463.4     .12       0   521.9     .06       0  541.36     .12       0
  551.65    .016       0   582.1     .06       0  633.84     .12       0
Bank Sta=303.9,463.4
XS Rating Curve= 0 ,0
Exp/Cntr=0.3,0.1

Type RM Length L Ch R = 1 ,30732   ,928.6,933.3,938
XS GIS Cut Line= 2
     1794301.302      207381.826     1794127.691      206444.326
#Sta/Elev= 30
       0 1478.21    19.7 1472.66    29.5 1468.11    39.3 1461.69      59 1446.25
    78.6 1432.72   127.8 1403.37  163.74 1383.98   176.9 1377.76   186.8 1374.57
  194.811373.712   255.6 1372.27  305.881368.473   324.4 1367.45   501.3 1367.39
  506.32 1367.79   540.6 1373.28  626.121377.598  653.431379.939  698.771392.195
   701.71392.682   707.7 1393.68   717.5 1393.88     747 1393.01  807.151401.392
   818.21402.976   835.5 1405.83  869.771412.992   914.1 1423.59   953.4    1436
#Mann= 14 ,-1 , 0
       0     .12       0  163.74    .016       0  194.81     .12       0
  305.88     .04       0   324.4    .045       0   501.3     .04       0
  506.32     .12       0  626.12    .016       0  653.43     .12       0
  698.77     .08       0   701.7     .12       0  807.15     .06       0
   818.2    .016       0  869.77     .06       0
Bank Sta=324.4,501.3
XS Rating Curve= 0 ,0
Exp/Cntr=0.3,0.1

Type RM Length L Ch R = 1 ,29798.7 ,701.8,701.9,702.1
XS GIS Cut Line= 2
     1795136.372      207453.874     1795166.754       206290.68
#Sta/Elev= 30
       0 1462.37    1.831461.815     9.8  1459.4    29.3 1455.46    37.51452.088
   146.7 1393.13   156.4 1388.32  168.931383.332   195.6  1375.2   205.3 1373.29
  218.011372.835  409.181367.958   430.2 1367.45     440 1367.43   606.2 1367.43
  615.29 1367.81   645.4 1374.03   733.4 1376.75   772.5 1379.71     792 1383.01
   821.4 1389.77  846.091393.671   850.7 1394.16  883.141390.857   928.9 1394.17
   948.5 1396.92   997.4 1409.32    1056 1426.24  1114.7 1438.94  1163.6 1453.69
#Mann= 11 ,-1 , 0
       0     .12       0    1.83    .016       0    37.5     .12       0
  168.93    .016       0  218.01     .12       0  409.18     .04       0
   430.2    .045       0   606.2     .08       0  615.29     .12       0
  846.09    .016       0  883.14     .12       0
Bank Sta=430.2,606.2
XS Rating Curve= 0 ,0
Exp/Cntr=0.3,0.1

Type RM Length L Ch R = 1 ,29096.8 ,452.1,452.7,453.3
XS GIS Cut Line= 3
     1795835.157      207435.645     1795865.539      206502.485
     1795804.775      206159.603
#Sta/Elev= 30
       0 1464.79    39.3 1450.23   94.211431.902   117.9 1428.25  127.991425.833
   196.6 1397.32   216.2 1390.41  249.531380.302   265.4 1375.62  285.741372.652
   339.61369.187   363.6 1367.43   373.5 1367.43     570 1367.52  579.25 1368.36
   609.3 1373.96   638.8 1375.88   668.3 1375.82  738.321372.743   775.31374.363
   825.6 1383.36   864.9  1392.5   874.7 1393.83     914 1393.64   923.8 1394.01
   933.6 1395.56  1030.4 1423.41  1127.1 1452.91  1252.9 1499.54  1281.9 1508.87
#Mann= 11 ,-1 , 0
       0     .12       0   94.21    .016       0  127.99     .12       0
  249.53    .016       0  285.74     .12       0   339.6     .04       0
   373.5    .045       0     570     .08       0  579.25     .12       0
  738.32    .016       0   775.3     .12       0
Bank Sta=373.5,570
XS Rating Curve= 0 ,0
Exp/Cntr=0.3,0.1

Type RM Length L Ch R = 1 ,28644.1 ,609.6,626.9,644.3
XS GIS Cut Line= 4
     1796184.462      207442.416     1796286.489      207218.328
     1796325.087      206580.437      1796614.15      206364.291
#Sta/Elev= 30
       0 1444.31    8.371443.129   85.861428.874   132.6 1419.22  158.461412.593
   179.9 1406.46   208.3 1404.62  224.461401.829   265.9  1391.1   285.6 1387.18
  371.511374.159   393.7 1369.17   413.4  1367.2   482.2 1366.94   619.8 1367.13
   750.9  1383.1  793.821387.365  823.441391.583  849.22 1392.57   885.3 1392.39
  963.321394.812   982.8 1398.21  1021.8 1409.85  1051.1 1417.12 1135.571429.993
  1158.4 1431.43 1181.831435.156    1217 1440.95  1226.7 1443.66  1246.2 1452.48
#Mann= 15 ,-1 , 0
       0     .12       0    8.37     .06       0   85.86     .12       0
  158.46    .016       0  224.46     .12       0  371.51     .04       0
   413.4    .045       0   619.8     .06       0   750.9    .016       0
  793.82     .06       0  823.44     .08       0  849.22     .06       0
  963.32     .12       0 1135.57    .016       0 1181.83     .12       0
Bank Sta=413.4,619.8
XS Rating Curve= 0 ,0
Exp/Cntr=0.3,0.1

Type RM Length L Ch R = 1 ,28017.2 ,450.1,468.4,486.7
XS GIS Cut Line= 2
     1796546.528      207478.035     1797141.146       206931.16
#Sta/Elev= 30
       0 1402.99    48.7 1399.44    58.4 1398.06   82.58 1392.02  107.631388.236
  117.621387.438   136.3 1386.11  165.581381.126   223.9 1371.82  280.251366.627
  285.391366.292   311.5 1365.69   457.5 1365.23   486.7 1365.24   496.4 1365.74
  506.111368.115   535.3  1381.7  553.811386.106  556.221386.409     584  1388.4
   596.51387.918   613.2 1385.62   622.9 1385.49  636.031387.775  640.911388.706
   652.1 1389.73  696.721390.373   720.3 1392.45  774.231400.021   807.9 1402.54
#Mann= 17 ,-1 , 0
       0     .06       0   82.58     .12       0  107.63     .08       0
  117.62    .016       0  165.58     .12       0  280.25     .08       0
  285.39     .04       0   311.5    .045       0   486.7     .04       0
  506.11     .12       0  553.81     .06       0  556.22    .016       0
   596.5     .06       0  636.03     .08       0  640.91     .06       0
  696.72    .016       0  774.23     .12       0
Bank Sta=311.5,486.7
XS Rating Curve= 0 ,0
Exp/Cntr=0.3,0.1