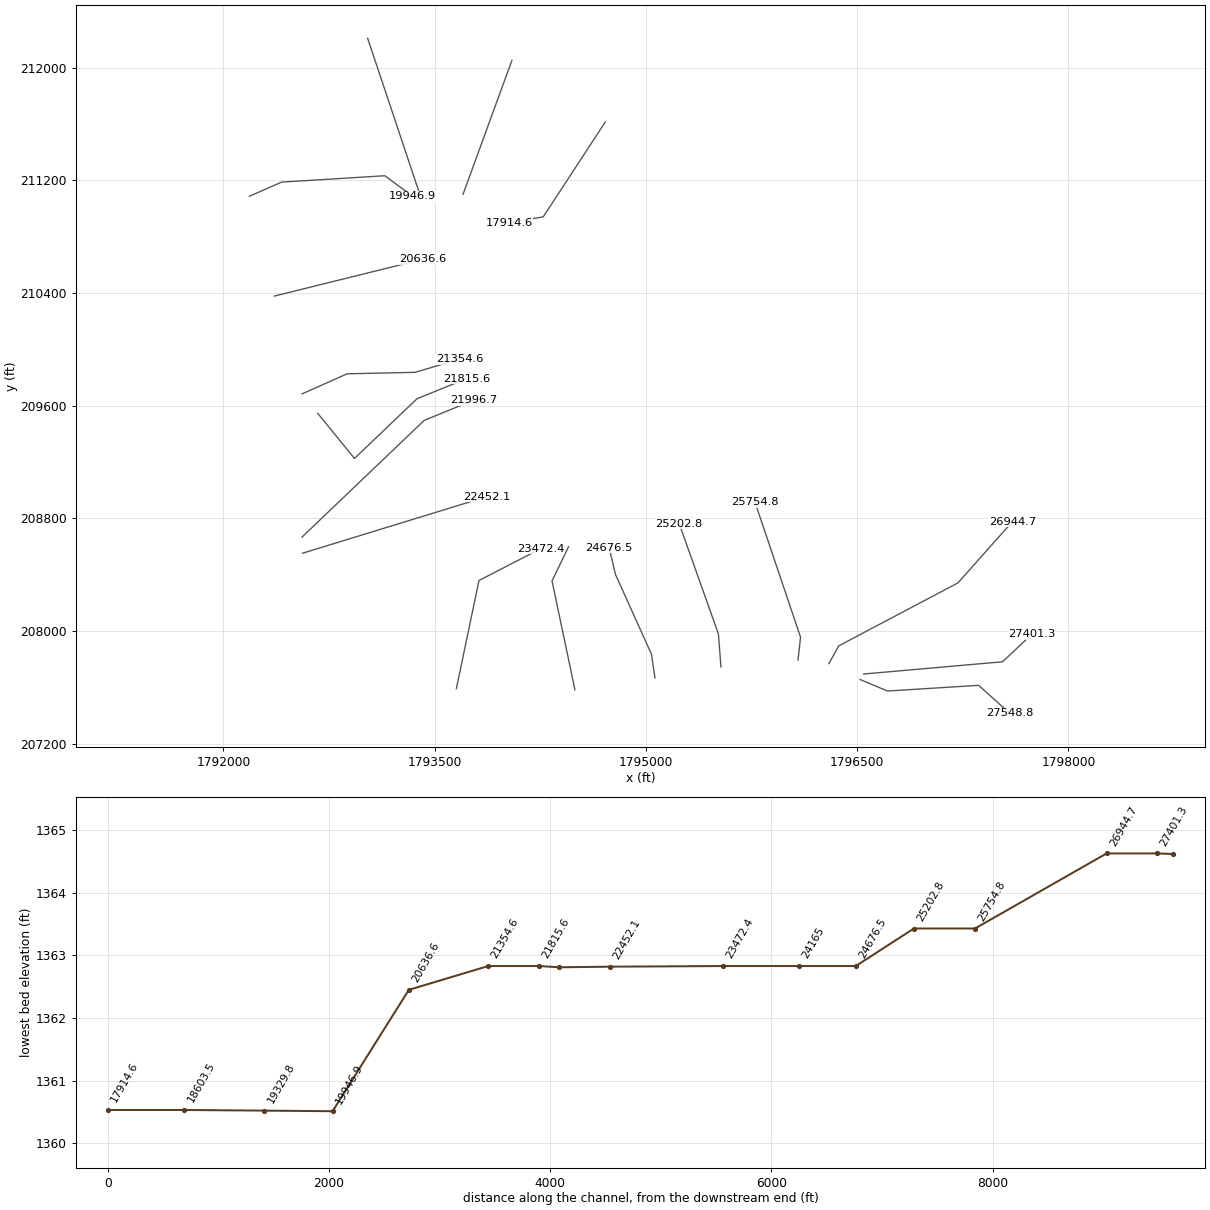
HEC-RAS study BUCKHANRV.prj: BUCKHANRV

--- BUCKHANRV.g01 (geometry) --- (continued)

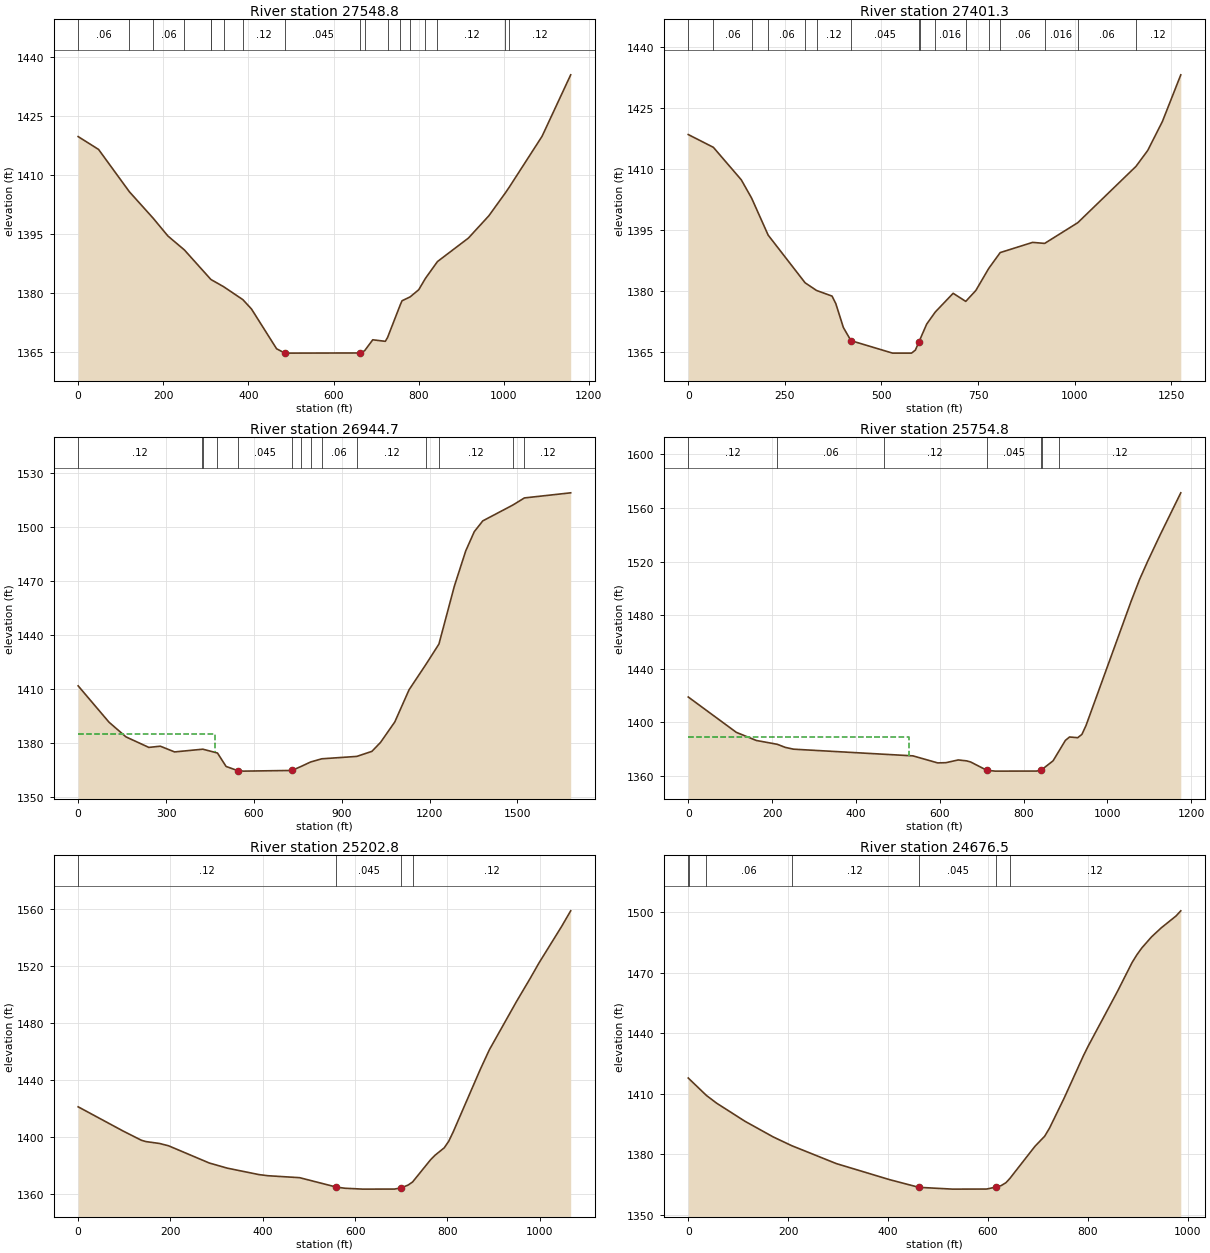
Type RM Length L Ch R = 1 ,27548.8 ,147.2,147.5,148.2
XS GIS Cut Line= 4
     1796521.355      207655.263     1796715.674      207573.408
     1797362.793      207613.857      1797584.61      207414.719
#Sta/Elev= 30
       0 1419.66    47.9  1416.4  120.241405.651  176.131398.924   210.9 1394.39
  249.661390.842  311.541383.381  312.091383.327  341.721381.509  387.06 1378.21
   407.3 1375.83   466.3 1365.72   485.9 1364.62   662.8 1364.66  673.131365.238
   692.2 1368.01   721.7 1367.62   726.91368.564  756.531376.803     761 1377.93
     7801378.914   800.3 1380.74  815.791383.593  844.181387.887   916.9 1393.86
     965 1399.53  1004.11405.396 1013.251406.854    1090 1419.73  1157.3 1435.36
#Mann= 18 ,-1 , 0
       0     .06       0  120.24    .016       0  176.13     .06       0
  249.66    .016       0  311.54     .06       0  312.09     .08       0
  341.72    .016       0  387.06     .12       0   485.9    .045       0
   662.8     .04       0  673.13     .12       0   726.9     .08       0
  756.53    .016       0     780     .12       0  815.79     .08       0
  844.18     .12       0  1004.1     .06       0 1013.25     .12       0
Bank Sta=485.9,662.8
XS Rating Curve= 0 ,0
Exp/Cntr=0.3,0.1

Type RM Length L Ch R = 1 ,27401.3 ,447.3,456.6,465.5
XS GIS Cut Line= 3
     1796547.396      207694.326     1797532.639      207781.131
     1797740.973      207976.444
#Sta/Elev= 30
       0  1418.4   64.991415.255   137.1 1407.28  163.941402.767  206.821393.654
  302.361381.934  332.06 1380.04   372.1 1378.66   381.9 1376.79   401.5 1370.91
   421.1  1367.7   528.8 1364.63   577.8 1364.63   587.6 1365.36   597.4 1367.43
  599.351367.918   616.9 1371.75  639.041374.723   685.5 1379.35  718.151377.359
   744.2 1380.04  777.541385.458  807.241389.364   891.1 1391.87  922.321391.623
 1007.941396.709 1158.571410.564    1189 1414.48    1227 1421.61  1274.6 1433.09
#Mann= 16 ,-1 , 0
       0     .12       0   64.99     .06       0  163.94    .016       0
  206.82     .06       0  302.36     .08       0  332.06     .12       0
   421.1    .045       0   597.4     .04       0  599.35     .08       0
  639.04    .016       0  718.15     .06       0  777.54     .08       0
  807.24     .06       0  922.32    .016       0 1007.94     .06       0
 1158.57     .12       0
Bank Sta=421.1,597.4
XS Rating Curve= 0 ,0
Exp/Cntr=0.3,0.1

Type RM Length L Ch R = 1 ,26944.7 ,1157.7,1189.9,1221.5
XS GIS Cut Line= 4
        1796300.       207768.11     1796369.445      207893.978
     1797215.799      208341.027     1797602.084      208775.055
#Sta/Elev= 30
       0 1411.95   105.4 1391.78   163.3 1383.63   241.4 1377.79   280.5 1378.47
   329.3 1375.29  424.071376.778  425.681376.801  475.821374.684   505.1 1367.23
   544.2 1364.94   563.7 1364.63   729.8    1365  761.111367.212  793.621369.689
  831.911371.472  951.361372.797  1003.2 1375.61  1032.6 1380.57  1081.4 1391.95
    1130 1409.77 1189.071424.221 1232.031435.156  1284.9  1467.4  1323.6 1486.88
  1352.7 1497.52  1381.8 1503.52 1484.621512.325 1524.01 1516.26    1682 1519.09
#Mann= 14 ,-1 , 0
       0     .12       0  424.07     .08       0  425.68    .016       0
  475.82     .12       0   544.2    .045       0   729.8     .04       0
  761.11     .06       0  793.62    .016       0  831.91     .06       0
  951.36     .12       0 1189.07    .016       0 1232.03     .12       0
 1484.62    .016       0 1524.01     .12       0
#XS Ineff= 2 , 0
          466.25 1385.41
Permanent Ineff=
       F       F
Bank Sta=544.2,729.8
XS Rating Curve= 0 ,0
Exp/Cntr=0.3,0.1

Type RM Length L Ch R = 1 ,25754.8 ,551.6,552,552.3
XS GIS Cut Line= 3
     1796080.295      207793.978     1796098.525      207955.437
     1795774.827      208914.667
#Sta/Elev= 30
       0  1418.8   114.7 1392.39   162.5 1386.32  212.331383.476   231.3 1381.18
   250.9 1379.83  465.981376.054     536 1374.83     595 1369.58   614.6 1369.74
   644.1 1371.78   663.8  1371.1   673.6 1370.26   712.51364.029   732.6 1363.43
   830.8 1363.48   840.7 1364.08  844.481364.836   870.2 1371.12  884.591378.584
   899.6 1386.38   909.5 1388.93   929.1 1388.41     939 1390.87   948.8 1397.48
  1056.9 1490.72  1076.6 1506.63  1096.2 1520.39  1125.7 1539.95  1174.9 1571.33
#Mann= 7 ,-1 , 0
       0     .12       0  212.33     .06       0  465.98     .12       0
   712.5    .045       0   840.7     .04       0  844.48    .016       0
  884.59     .12       0
#XS Ineff= 2 , 0
          527.55 1388.85
Permanent Ineff=
       F       F
Bank Sta=712.5,840.7
XS Rating Curve= 0 ,0
Exp/Cntr=0.3,0.1

Type RM Length L Ch R = 1 ,25202.8 ,524.5,526.3,528.2
XS GIS Cut Line= 3
      1795533.42      207744.499     1795515.191      207978.874
     1795236.632      208762.757
#Sta/Elev= 30
       0  1421.1      98 1404.03   137.1 1397.66   146.9 1396.74   176.3 1395.42
   195.9 1393.79     284 1381.74   323.2 1378.12   391.7 1373.61   411.2 1372.82
   479.8 1371.45   559.4 1364.86   577.6 1364.06   616.8 1363.43   685.3 1363.47
   699.41364.292   714.6 1366.24  724.461368.444   763.6 1384.07   773.4 1387.26
     793 1392.36   802.7 1396.94   812.5 1403.54   871.2 1447.37   890.8 1461.08
   949.5 1494.84   978.9 1510.91   998.5 1522.02  1047.4 1547.53    1067 1558.44
#Mann= 4 ,-1 , 0
       0     .12       0   559.4    .045       0   699.4    .016       0
  724.46     .12       0
Bank Sta=559.4,699.4
XS Rating Curve= 0 ,0
Exp/Cntr=0.3,0.1

Type RM Length L Ch R = 1 ,24676.5 ,516.4,511.6,506.7
XS GIS Cut Line= 4
      1795064.67      207666.374      1795039.74      207834.972
     1794784.448      208401.212      1794739.15      208590.853
#Sta/Elev= 30
       0 1417.84    1.03 1417.58   36.361409.214    56.8 1405.39   113.6 1396.42
   170.4 1388.64  207.031384.364   296.6 1375.47   403.4 1367.51     4621363.717
   529.5 1362.83   597.5 1362.87   616.9 1363.88   626.6 1364.56   636.3 1366.01
  644.06 1368.09   694.5 1384.05   713.9 1389.03   723.6 1393.05   752.7  1407.8
   791.6 1428.95   801.3 1433.77   859.8 1460.78     889 1475.04   898.8 1478.94
   908.6 1482.28     928 1487.74   947.5 1492.21   976.8 1498.02   986.5 1500.61
#Mann= 7 ,-1 , 0
       0     .06       0    1.03    .016       0   36.36     .06       0
  207.03     .12       0     462    .045       0   616.9    .016       0
  644.06     .12       0
Bank Sta=462,616.9
XS Rating Curve= 0 ,0
Exp/Cntr=0.3,0.1

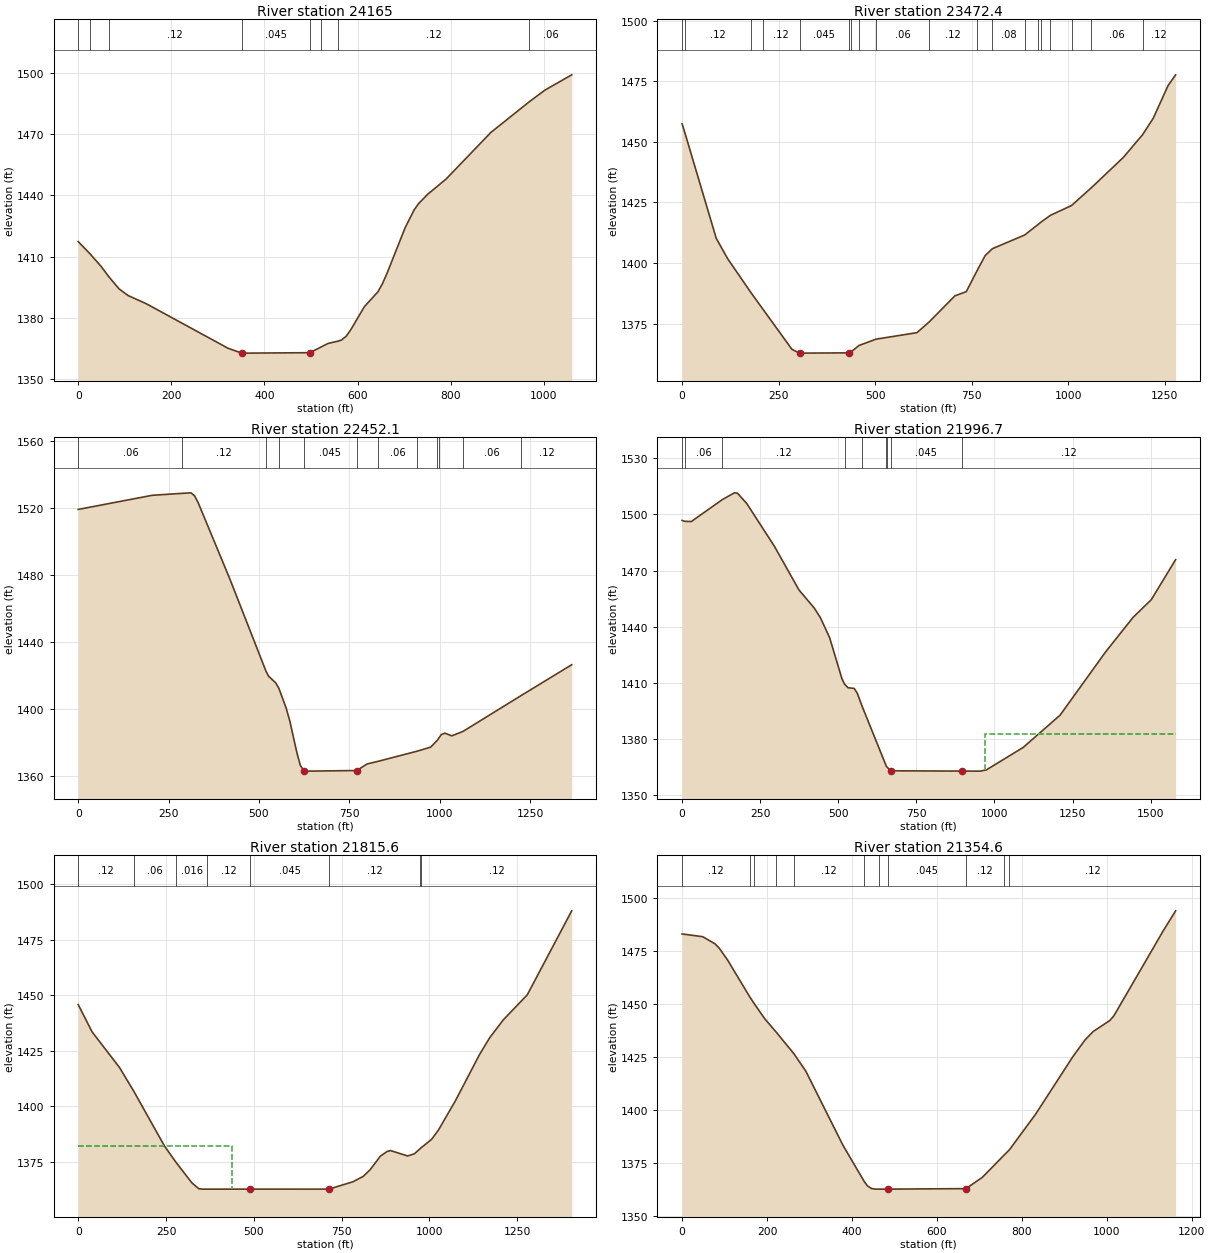
Type RM Length L Ch R = 1 ,24165   ,701.9,692.6,683.3
XS GIS Cut Line= 3
     1794496.615      207581.478     1794333.855      208354.771
     1794451.042      208597.827
#Sta/Elev= 30
       0  1417.4   25.191411.479    48.8 1405.36   66.231400.087    87.8 1394.25
   107.3    1391   146.3    1387     322  1365.2   350.81362.884     361 1362.83
   497.6 1363.04  521.88 1365.85   536.6 1367.57  558.311368.699   565.8 1369.27
   575.6 1371.08   585.4 1374.23   614.6 1385.51   643.9 1392.85   653.6 1396.85
   663.4 1401.89   702.4 1424.26   721.9 1433.05   731.7 1436.13   751.2 1440.65
   790.2    1448   886.6 1470.86  969.251485.872  1002.2 1491.47  1060.1 1499.01
#Mann= 8 ,-1 , 0
       0     .12       0   25.19    .016       0   66.23     .12       0
   350.8    .045       0   497.6     .12       0  521.88    .016       0
  558.31     .12       0  969.25     .06       0
Bank Sta=350.8,497.6
XS Rating Curve= 0 ,0
Exp/Cntr=0.3,0.1

Type RM Length L Ch R = 1 ,23472.4 ,1044.4,1020.3,996.2
XS GIS Cut Line= 3
     1793654.601      207590.159     1793815.191      208358.388
     1794253.559      208584.082
#Sta/Elev= 30
       0 1457.39    7.661453.458    88.3 1410.22   117.7 1401.84  179.191387.577
  208.341381.154   284.5 1364.37   304.1 1362.83   431.7 1362.94  436.741363.233
  457.881365.981  502.371368.598   608.2 1371.28  639.971375.731   706.4 1386.46
   735.8  1388.2  764.091396.928   784.8 1403.09  803.441405.916  886.811411.544
  920.321415.715  929.271416.871  953.831419.689 1008.441423.732 1059.761431.068
  1142.5 1443.56 1192.461452.961  1219.9 1459.71  1258.6 1473.28  1277.9 1477.64
#Mann= 19 ,-1 , 0
       0    .016       0    7.66     .12       0  179.19    .016       0
  208.34     .12       0   304.1    .045       0   431.7     .04       0
  436.74     .12       0  457.88    .016       0  502.37     .06       0
  639.97     .12       0  764.09    .016       0  803.44     .08       0
  886.81     .06       0  920.32    .016       0  929.27     .08       0
  953.83    .016       0 1008.44     .12       0 1059.76     .06       0
 1192.46     .12       0
Bank Sta=304.1,431.7
XS Rating Curve= 0 ,0
Exp/Cntr=0.3,0.1

Type RM Length L Ch R = 1 ,22452.1 ,443.3,455.4,467.5
XS GIS Cut Line= 3
     1792562.696       208551.94     1793215.184      208752.105
     1793867.672      208952.269
#Sta/Elev= 30
       0 1519.16   204.8 1527.59  288.211528.773     312 1529.07   321.8 1527.27
   331.5 1523.33   419.2 1477.74  519.371422.532   526.5 1419.54     546 1415.63
  555.061412.302   575.2 1400.45     585    1393   604.5 1374.16   614.2 1366.36
     624  1363.1   633.8 1362.82   770.2 1363.17   799.5 1367.13  830.021368.698
  937.651374.743     975 1377.15   993.71381.363  998.861382.972  1004.2 1384.64
    1014 1385.51  1033.5  1383.9 1064.411386.558 1225.891408.066    1365 1426.38
#Mann= 12 ,-1 , 0
       0     .06       0  288.21     .12       0  519.37    .016       0
  555.06     .12       0     624    .045       0   770.2     .12       0
  830.02     .06       0  937.65     .12       0   993.7     .08       0
  998.86     .12       0 1064.41     .06       0 1225.89     .12       0
Bank Sta=624,770.2
XS Rating Curve= 0 ,0
Exp/Cntr=0.3,0.1

Type RM Length L Ch R = 1 ,21996.7 ,180.7,181.1,181.4
XS GIS Cut Line= 3
     1792558.681      208666.548     1793426.736      209495.541
     1793778.299       209638.77
#Sta/Elev= 30
       0 1496.81    8.351496.358    29.5 1496.24  128.481507.929   167.3 1511.58
   177.1 1511.39   206.6 1505.95   295.2 1483.08   373.9 1459.71   423.1 1449.97
   442.7 1444.84   472.2 1434.18   511.6 1412.24  519.861409.315   531.3 1407.39
     551 1407.02   560.8 1404.43  576.471397.395  653.731365.474  655.19 1365.08
     669 1362.98   895.3 1362.83   954.4 1362.81     974 1363.46  1092.1  1375.5
    1210 1392.73    1356 1426.59  1443.7    1445  1502.1 1454.47  1579.9 1475.86
#Mann= 9 ,-1 , 0
       0     .12       0    8.35     .06       0  128.48     .12       0
  519.86    .016       0  576.47     .12       0  653.73     .08       0
  655.19     .04       0     669    .045       0   895.3     .12       0
#XS Ineff= 2 , 0
                           970.9          1382.7
Permanent Ineff=
       F       F
Bank Sta=669,895.3
XS Rating Curve= 0 ,0
Exp/Cntr=0.3,0.1

Type RM Length L Ch R = 1 ,21815.6 ,479.7,461,442.3
XS GIS Cut Line= 4
      1792670.66      209544.586     1792931.214      209224.834
     1793374.653      209648.319     1793726.216      209791.548
#Sta/Elev= 30
       0  1445.8    39.3  1433.6   117.8 1417.48  158.861406.686   245.5 1382.27
   278.2 1374.94   324.1 1365.58   343.7    1363   353.5 1362.83  367.75 1362.83
   490.3 1362.83   714.2 1362.84   782.3 1366.14   811.5 1368.55     831 1371.49
   860.2 1377.62   879.6 1379.76   889.4 1380.17     938 1377.74   957.5 1378.73
  972.621380.886  977.221381.507  1006.2  1385.2  1025.6 1389.34  1074.3 1402.61
  1142.4 1423.23  1171.6 1430.87  1210.6 1438.97  1278.7 1450.18  1405.3 1487.97
#Mann= 8 ,-1 , 0
       0     .12       0  158.86     .06       0   278.2    .016       0
  367.75     .12       0   490.3    .045       0   714.2     .12       0
  972.62     .06       0  977.22     .12       0
#XS Ineff= 2 , 0
          439.22 1382.23
Permanent Ineff=
       F       F
Bank Sta=490.3,714.2
XS Rating Curve= 0 ,0
Exp/Cntr=0.3,0.1

Type RM Length L Ch R = 1 ,21354.6 ,713.1,718,723
XS GIS Cut Line= 4
     1792559.549      209683.475     1792878.993      209825.836
     1793361.632      209836.253     1793677.605      209930.003
#Sta/Elev= 30
       0 1482.92    48.6 1481.62    77.7 1478.25    87.4 1476.21   106.9  1470.7
  159.091453.383  169.961450.077   194.3 1443.08  221.511436.729  263.191426.573
   291.4 1418.31   378.7 1383.48  429.221366.295   436.6 1364.35   446.3 1363.08
   455.9 1362.83   463.2 1362.83   484.9 1362.83   668.4 1363.06     707 1368.39
  757.671378.737  770.891381.381   832.5 1398.13   919.7 1425.05   948.8 1433.05
   968.2 1437.04    1007 1442.16  1016.7 1444.39    1133 1484.41  1162.1  1493.8
#Mann= 11 ,-1 , 0
       0     .12       0  159.09     .06       0  169.96     .12       0
  221.51     .06       0  263.19     .12       0  429.22    .016       0
   463.2     .12       0   484.9    .045       0   668.4     .12       0
  757.67     .06       0  770.89     .12       0
Bank Sta=484.9,668.4
XS Rating Curve= 0 ,0
Exp/Cntr=0.3,0.1

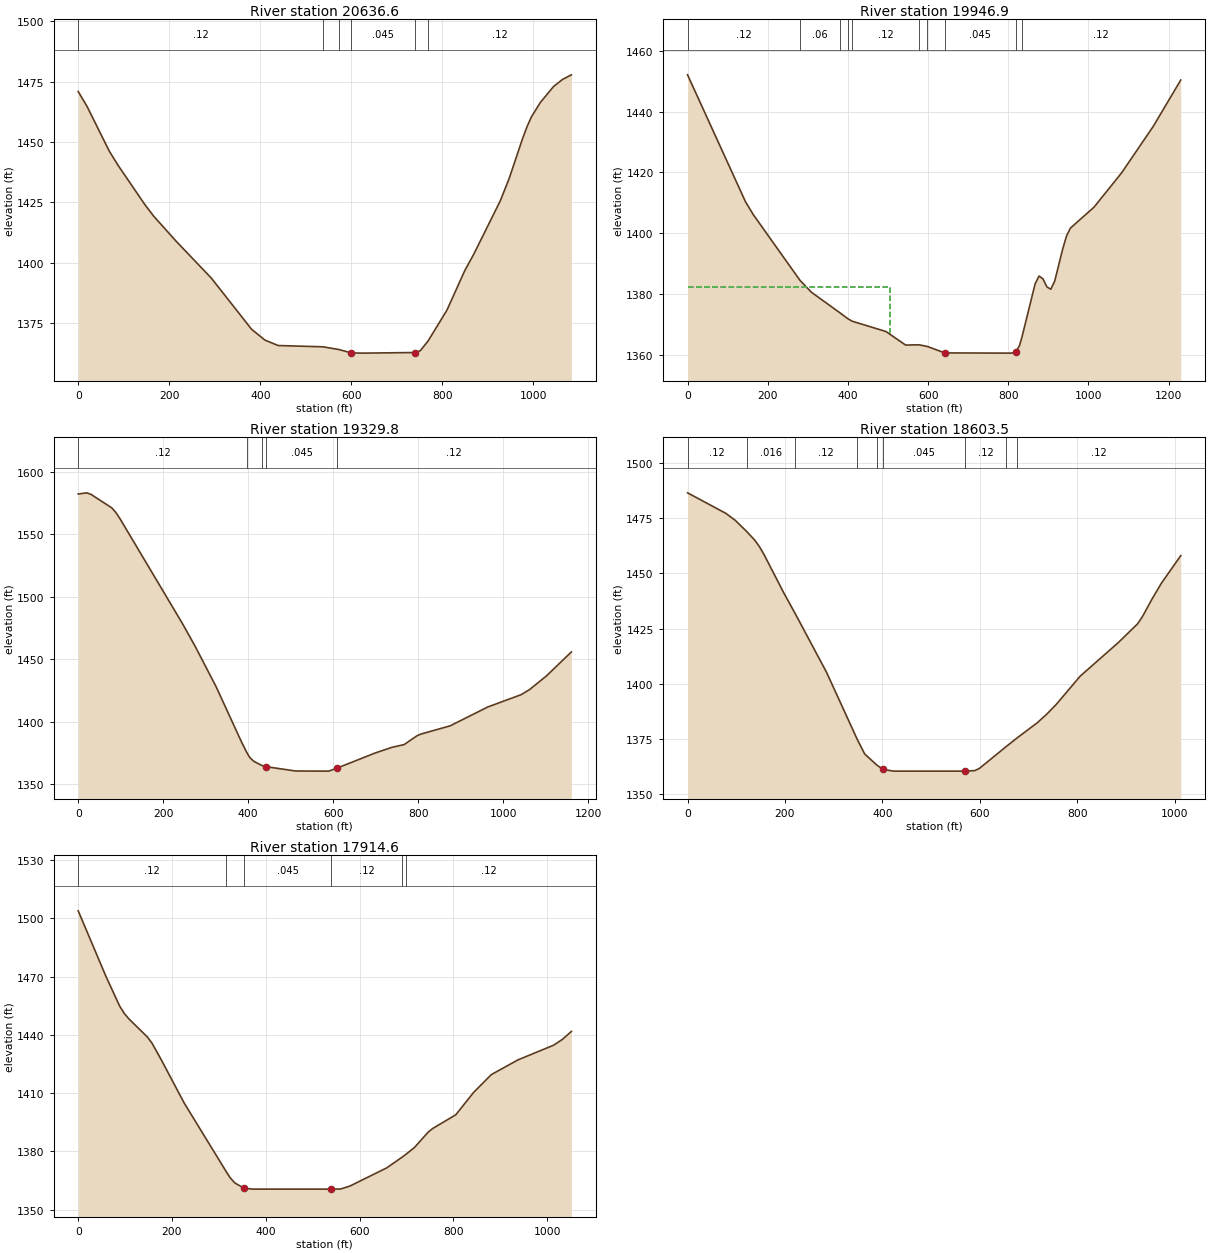
Type RM Length L Ch R = 1 ,20636.6 ,693.7,689.7,685.6
XS GIS Cut Line= 2
     1792362.082      210377.618     1793413.716      210638.336
#Sta/Elev= 30
       0 1470.92    19.5 1464.74    68.3 1446.21    87.8 1440.27   146.4 1424.06
   165.9 1419.23   214.7 1408.95   292.8 1393.49   380.7 1372.39     410 1367.88
   439.2  1365.6   537.81365.066  572.231363.958   600.41362.534   624.7 1362.45
   740.4  1362.7   751.6 1363.46  768.831367.542   810.2 1380.31   849.2 1396.65
   868.7 1403.35   927.3 1425.61   946.8 1434.87   976.1 1451.32   985.9  1456.3
   995.6 1460.39  1015.1 1466.34  1044.4 1473.02    1064 1475.94  1083.5 1477.85
#Mann= 6 ,-1 , 0
       0     .12       0   537.8    .016       0  572.23     .12       0
   600.4    .045       0   740.4     .04       0  768.83     .12       0
Bank Sta=600.4,740.4
XS Rating Curve= 0 ,0
Exp/Cntr=0.3,0.1

Type RM Length L Ch R = 1 ,19946.9 ,646.8,617.2,587.6
XS GIS Cut Line= 4
     1792184.549      211086.253     1792413.716      211186.947
     1793146.355      211232.086     1793344.271      211086.253
#Sta/Elev= 30
       0 1452.12   144.4 1410.37   163.7 1406.15  280.271384.497     309 1380.55
  381.34 1373.66   400.61371.767  410.641371.019     495 1367.62   543.9 1363.16
  576.771363.256  598.081362.704   641.8 1360.58   808.2 1360.51     818 1360.84
   827.8 1362.92  834.141365.809   866.9 1383.28   876.7 1385.88   886.5 1384.96
   896.3 1382.31     906 1381.54   915.8 1384.22   935.4 1394.63   945.2 1399.05
     955 1401.67  1013.8 1408.55  1082.7 1419.86  1161.4 1435.11  1230.2 1450.41
#Mann= 10 ,-1 , 0
       0     .12       0  280.27     .06       0  381.34     .12       0
   400.6     .06       0  410.64     .12       0  576.77    .016       0
  598.08     .12       0   641.8    .045       0     818     .04       0
  834.14     .12       0
#XS Ineff= 2 , 0
          504.23 1382.13
Permanent Ineff=
       F       F
Bank Sta=641.8,818
XS Rating Curve= 0 ,0
Exp/Cntr=0.3,0.1

Type RM Length L Ch R = 1 ,19329.8 ,741.5,726.3,711.1
XS GIS Cut Line= 2
     1793024.827       212207.78     1793392.882      211107.086
#Sta/Elev= 30
       0 1582.11    19.7 1583.05    29.5 1581.94    78.7 1571.11    88.5  1567.4
    98.4 1562.34   245.9 1478.17   275.4 1460.21   324.6 1427.99   383.6 1384.38
  396.491375.607   403.3 1371.59   413.1  1368.4   431.71365.121   442.31364.068
   511.4 1360.62   580.3 1360.52   590.1 1360.59   609.8    1363   698.3 1374.96
   737.7 1379.48   767.2 1381.77   796.7 1388.68   806.5 1390.14   875.4 1396.75
   963.9 1411.82  1042.6 1421.69  1062.2 1425.74  1101.6 1436.56  1160.6 1455.84
#Mann= 5 ,-1 , 0
       0     .12       0  396.49    .016       0   431.7     .04       0
   442.3    .045       0   609.8     .12       0
Bank Sta=442.3,609.8
XS Rating Curve= 0 ,0
Exp/Cntr=0.3,0.1

Type RM Length L Ch R = 1 ,18603.5 ,694.1,688.9,683.7
XS GIS Cut Line= 2
     1794049.132       212051.53      1793701.91      211100.142
#Sta/Elev= 30
       0 1486.52    78.7 1477.22    98.3    1474  121.351469.031   137.7 1465.17
   147.5  1462.2   157.3 1458.49   196.6 1441.64  221.341431.725   285.2 1405.37
  348.441374.929   363.8 1368.28  388.341363.347   401.11361.339   422.8 1360.53
   570.3 1360.53     590 1360.77   599.8 1361.84  654.781371.731  677.051375.616
   717.8 1382.36   737.4 1386.26   757.1 1390.73   806.3 1403.53     885 1418.81
   924.3 1427.25   934.1 1430.46   953.8 1438.44   973.4 1445.72  1012.8 1458.08
#Mann= 9 ,-1 , 0
       0     .12       0  121.35    .016       0  221.34     .12       0
  348.44    .016       0  388.34     .04       0   401.1    .045       0
   570.3     .12       0  654.78     .08       0  677.05     .12       0
Bank Sta=401.1,570.3
XS Rating Curve= 0 ,0
Exp/Cntr=0.3,0.1

Type RM Length L Ch R = 1 ,17914.6 ,600.6,602.4,604.3
XS GIS Cut Line= 3
     1794712.327       211614.03     1794271.355      210940.419
     1794028.299      210898.753
#Sta/Elev= 30
       0 1503.91    58.9 1470.29    88.4 1454.84    98.2 1451.07     108 1448.27
   147.3 1438.96   157.1 1435.85   176.7 1427.38   225.8 1404.98   315.11369.761
     324 1366.41   333.8 1363.76   353.5 1361.01   373.1 1360.53     540 1360.53
   559.6 1360.59   579.3  1362.1   657.8 1371.47  690.151376.893  699.391378.579
   716.8 1381.93   746.2 1389.87     756 1391.78   805.1 1398.82     843 1410.31
     881 1419.54   937.9 1427.13  1013.8 1434.68  1032.8 1437.73  1051.7 1441.78
#Mann= 6 ,-1 , 0
       0     .12       0   315.1    .016       0   353.5    .045       0
     540     .12       0  690.15     .08       0  699.39     .12       0
Bank Sta=353.5,540
XS Rating Curve= 0 ,0
Exp/Cntr=0.3,0.1