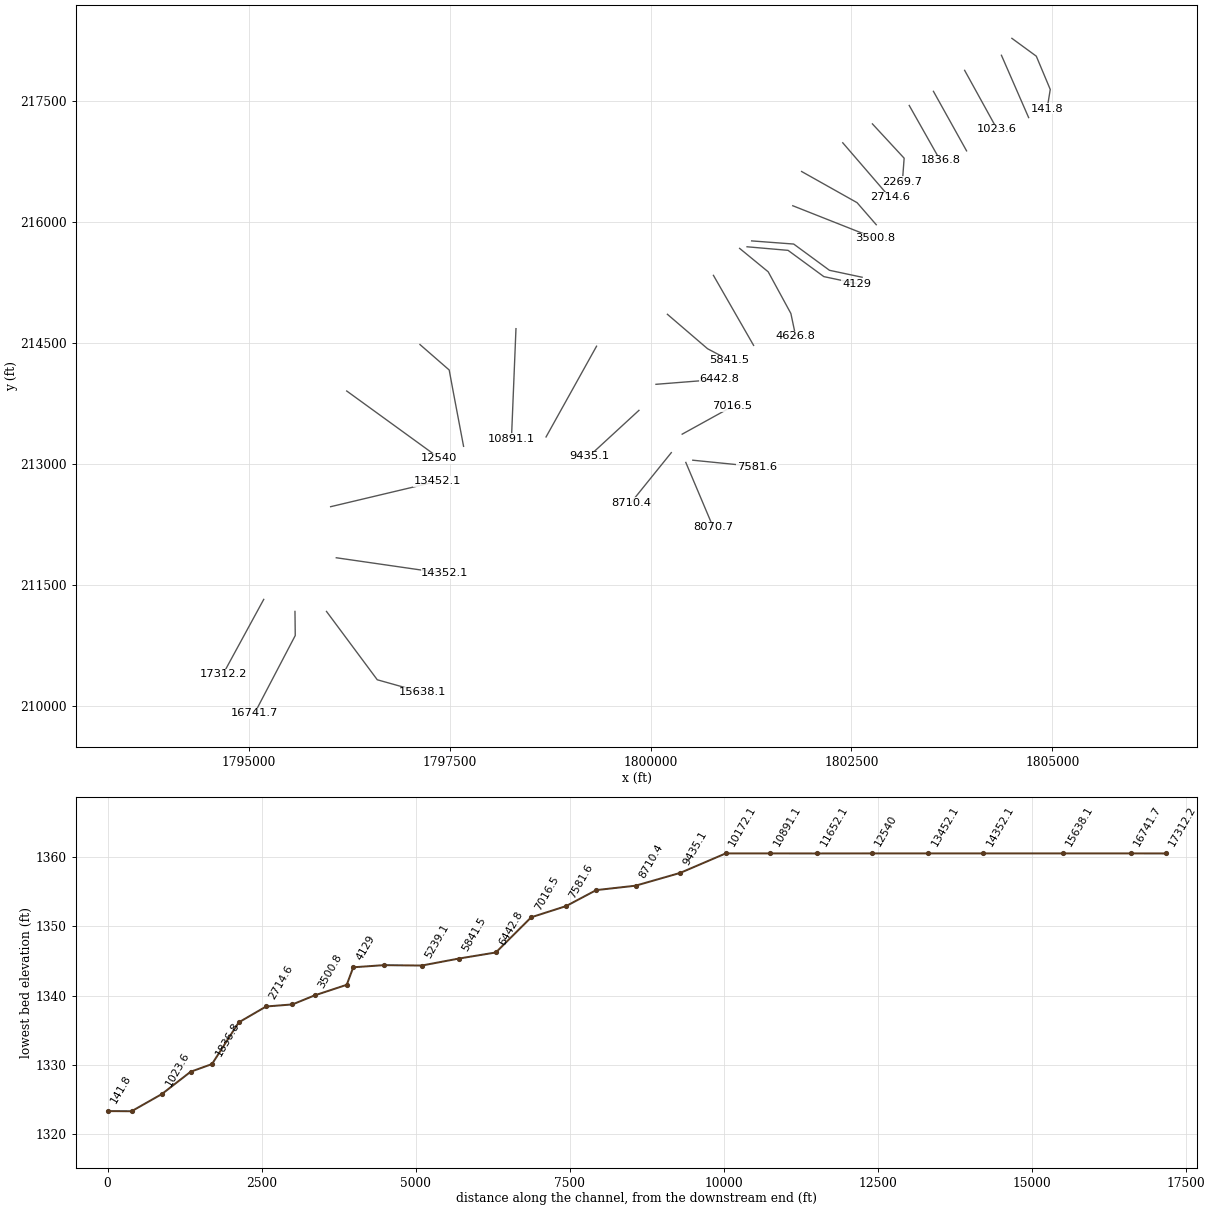
HEC-RAS study BUCKHANRV.prj: BUCKHANRV

--- BUCKHANRV.g01 (geometry) --- (continued)

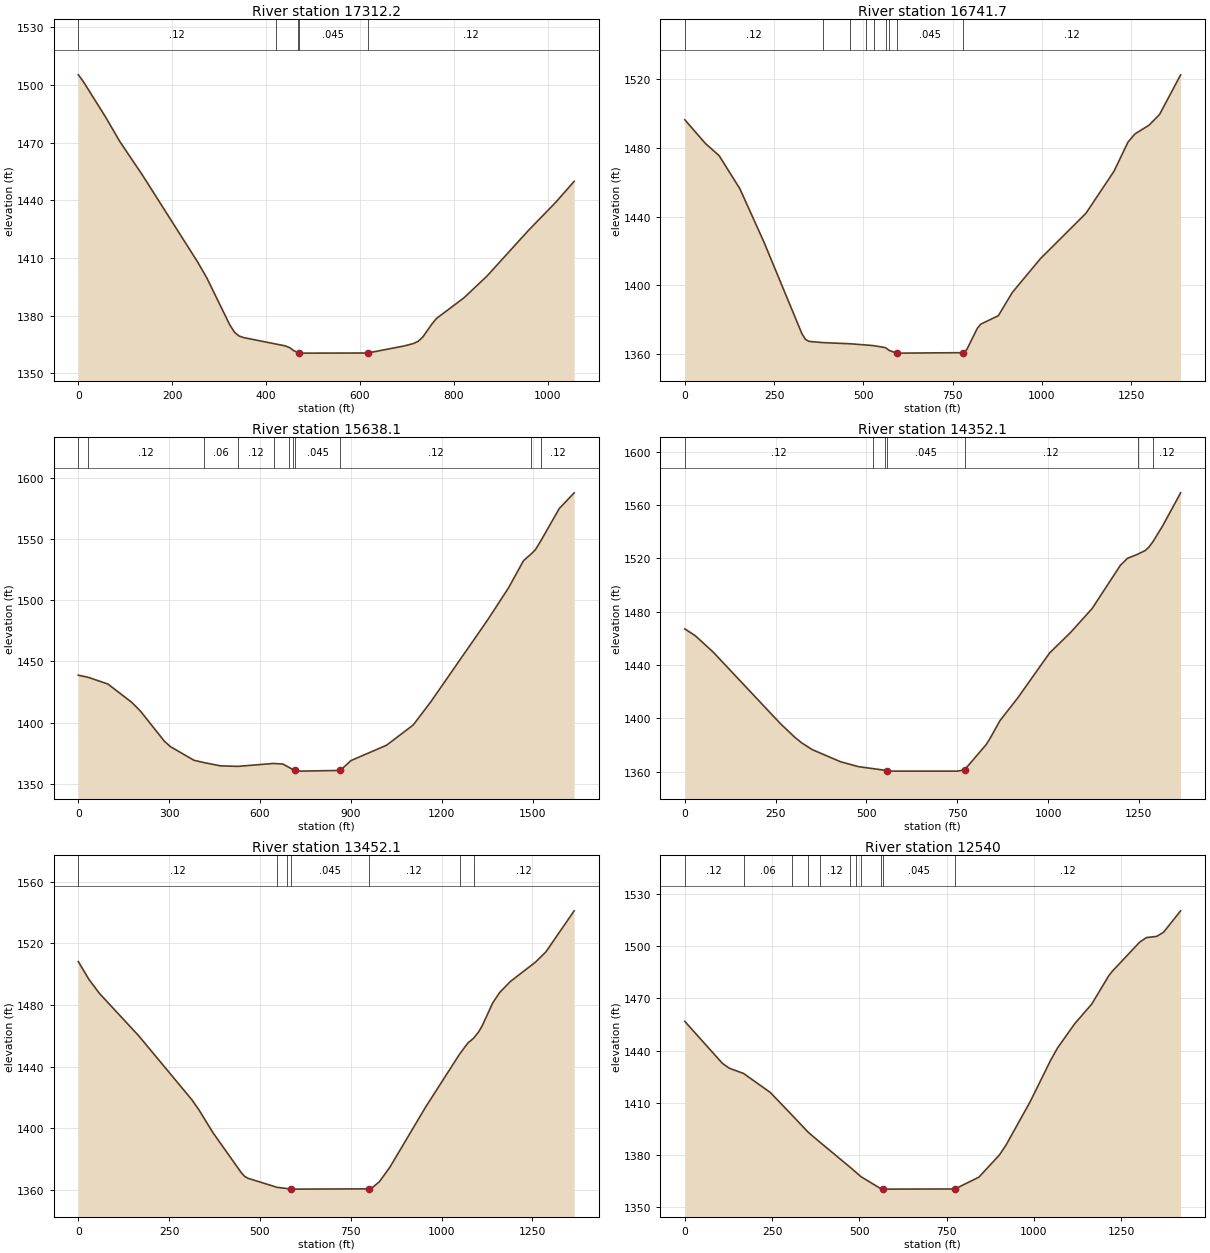
Type RM Length L Ch R = 1 ,17312.2 ,570.2,570.5,570.8
XS GIS Cut Line= 2
     1795184.549      211325.836     1794677.605      210398.753
#Sta/Elev= 30
       0  1505.3     9.8 1502.12    58.7  1483.1      88 1470.77     137    1453
   254.4 1407.87   273.9 1399.61   322.9 1375.15   332.6 1371.47   342.4 1369.42
   352.2 1368.61  420.88 1365.25   440.3 1364.32     450  1363.4   459.8 1361.71
  468.731360.753     4701360.654   479.4 1360.52   616.4 1360.58   694.6 1364.26
   714.2 1365.52     724 1366.65   733.8 1368.81   753.3 1375.61   763.1 1378.54
   821.8  1389.3   870.7 1400.57   958.8 1424.26  1017.5 1439.02  1056.6  1449.9
#Mann= 5 ,-1 , 0
       0     .12       0  420.88    .016       0  468.73     .04       0
     470    .045       0   616.4     .12       0
Bank Sta=470,616.4
XS Rating Curve= 0 ,0
Exp/Cntr=0.3,0.1

Type RM Length L Ch R = 1 ,16741.7 ,1078.2,1103.6,1129
XS GIS Cut Line= 3
     1795573.438       211176.53      1795576.91      210877.919
     1795069.966      209912.642
#Sta/Elev= 30
       0 1496.46    57.8 1482.63    96.3 1475.52   154.1 1456.33   221.6 1425.29
   328.1 1371.84   337.9 1368.58   347.7 1367.38  387.481366.653  462.991365.983
  507.221365.263  529.151364.888  562.221363.709  572.831362.079   593.3 1360.56
   603.1 1360.53   779.9  1360.8   789.8 1362.54   819.2 1374.92     829  1377.4
   878.2 1382.32   917.4 1395.85     996 1415.52  1123.7 1441.97  1202.3 1466.47
  1241.6 1483.48  1261.2 1488.23  1300.5 1493.31    1330 1499.56  1388.9 1522.62
#Mann= 9 ,-1 , 0
       0     .12       0  387.48     .06       0  462.99     .08       0
  507.22     .12       0  529.15    .016       0  562.22     .12       0
  572.83     .04       0   593.3    .045       0   779.9     .12       0
Bank Sta=593.3,779.9
XS Rating Curve= 0 ,0
Exp/Cntr=0.3,0.1

Type RM Length L Ch R = 1 ,15638.1 ,1268.1,1286,1303.8
XS GIS Cut Line= 3
     1795965.799       211176.53     1796597.743      210329.308
     1797156.771      210173.058
#Sta/Elev= 30
       0 1438.83   33.351437.022    97.9 1431.58   176.2  1416.7   205.5 1409.42
   283.8 1385.07   303.4 1380.63   381.7 1369.42  413.621367.566   469.8 1364.82
     5281364.415  644.981366.809   675.3 1366.32  694.361363.776  710.021361.608
   714.4 1361.09     734 1360.53   865.1  1361.1   900.4 1369.14  1017.8 1381.66
  1106.1 1398.23  1165.2 1417.52  1352.1 1484.05    1421 1510.24  1470.2 1532.29
 1496.311537.967  1509.5 1541.29 1526.931548.272  1588.2 1574.81  1637.4 1587.64
#Mann= 11 ,-1 , 0
       0     .06       0   33.35     .12       0  413.62     .06       0
     528     .12       0  644.98    .016       0  694.36     .12       0
  710.02     .04       0   714.4    .045       0   865.1     .12       0
 1496.31    .016       0 1526.93     .12       0
Bank Sta=714.4,865.1
XS Rating Curve= 0 ,0
Exp/Cntr=0.3,0.1

Type RM Length L Ch R = 1 ,14352.1 ,891.5,900,908.5
XS GIS Cut Line= 3
     1796087.677       211841.97     1796763.219      211744.762
     1797438.761      211647.555
#Sta/Elev= 30
       0 1467.11    29.2 1461.92      78 1449.76   263.2 1396.13   302.2 1386.05
   321.8 1381.72     351 1376.62     429 1367.54   477.8 1363.91  519.061362.357
  550.141361.213   555.8 1360.89   575.2 1360.53   750.8 1360.53   770.2 1361.51
   828.8 1380.11   838.5 1384.16   867.8 1398.41   916.5 1415.36  1004.2 1449.03
  1062.8 1464.63  1121.2 1482.29  1199.2 1514.76  1218.8 1519.96 1246.82 1523.04
  1267.5 1525.81  1277.2 1528.25  1288.61532.321  1316.2  1544.6    1365 1569.04
#Mann= 7 ,-1 , 0
       0     .12       0  519.06    .016       0  550.14     .12       0
   555.8    .045       0   770.2     .12       0 1246.82    .016       0
  1288.6     .12       0
Bank Sta=555.8,770.2
XS Rating Curve= 0 ,0
Exp/Cntr=0.3,0.1

Type RM Length L Ch R = 1 ,13452.1 ,931.5,912.1,892.8
XS GIS Cut Line= 3
     1796017.188      212475.087     1796681.358      212632.201
     1797345.528      212789.314
#Sta/Elev= 30
       0  1508.1    29.2 1496.55    58.5 1487.34   165.8 1460.08     312 1418.66
   331.5 1412.15   370.5 1397.19   448.5 1371.24   458.2 1368.71     468  1367.5
   547.31361.683  573.341360.952     585 1360.55   594.8 1360.53   799.5  1360.7
   809.2 1361.47   828.8 1365.33     858 1374.88   955.5 1413.52 1049.36 1447.98
  1072.5 1455.31 1087.921458.329  1101.8 1462.41  1111.5 1466.28  1140.8 1481.26
  1160.2  1488.1  1189.5 1495.19  1257.8 1507.59    1287 1514.32    1365    1541
#Mann= 7 ,-1 , 0
       0     .12       0   547.3    .016       0  573.34     .08       0
     585    .045       0   799.5     .12       0 1049.36    .016       0
 1087.92     .12       0
Bank Sta=585,799.5
XS Rating Curve= 0 ,0
Exp/Cntr=0.3,0.1

Type RM Length L Ch R = 1 ,12540   ,905.1,887.9,870.7
XS GIS Cut Line= 2
     1796217.643      213909.506     1797369.464      213077.476
#Sta/Elev= 30
       0 1456.75   107.8 1432.68   127.4  1429.9  168.491426.873     245 1415.99
  307.331402.974  354.081393.075  387.161387.465  473.791373.076     491 1370.11
  504.88 1367.67  561.55 1360.82   568.4 1360.54   578.2 1360.53   774.2 1360.62
   842.7 1367.39   901.5  1380.1   921.1 1385.99   989.7 1410.66  1048.5 1434.48
  1068.1 1441.49  1117.1 1455.33  1166.1 1466.67  1215.1 1482.99  1224.9 1485.48
  1303.3 1502.17  1322.9 1504.84  1352.3 1505.51  1371.9 1507.87  1420.9 1520.18
#Mann= 11 ,-1 , 0
       0     .12       0  168.49     .06       0  307.33     .12       0
  354.08    .016       0  387.16     .12       0  473.79     .06       0
     491     .12       0  504.88    .016       0  561.55     .04       0
   568.4    .045       0   774.2     .12       0
Bank Sta=568.4,774.2
XS Rating Curve= 0 ,0
Exp/Cntr=0.3,0.1

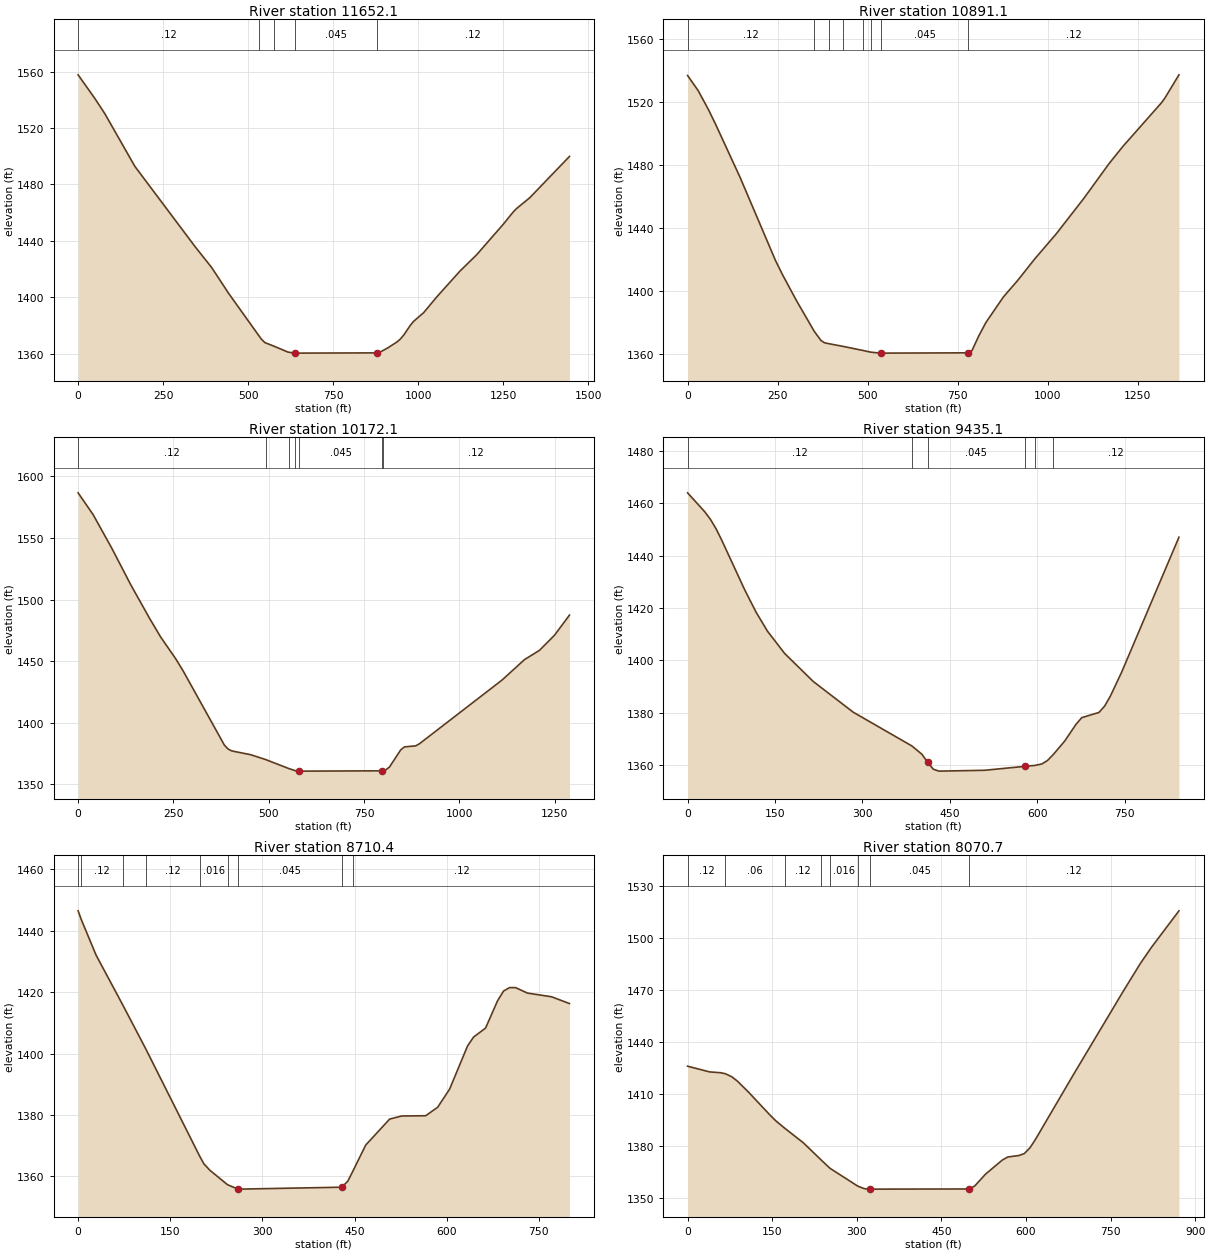
Type RM Length L Ch R = 1 ,11652.1 ,766.1,761,755.9
XS GIS Cut Line= 4
     1797128.993      214485.558     1797492.845      214170.097
     1797544.336      213894.068     1797671.876      213223.585
#Sta/Elev= 30
       0  1557.7    49.1    1541    78.6 1530.17   167.1 1492.78     344 1435.96
   393.1 1421.06   442.2 1403.02  532.611372.534   539.7 1370.21   549.3 1367.98
  574.661365.565   617.1 1361.27   636.5 1360.52   879.4  1360.7   889.1  1361.4
   908.6 1363.93   937.9 1368.47   947.6 1370.51   957.4 1373.26   976.9 1380.21
   986.6 1383.03  1015.9 1389.13  1054.9 1400.41  1123.1 1418.71  1171.9  1430.2
  1249.9 1451.72  1279.1 1460.41  1288.9 1462.88  1327.9 1470.57  1444.9 1499.88
#Mann= 5 ,-1 , 0
       0     .12       0  532.61    .016       0  574.66     .12       0
   636.5    .045       0   879.4     .12       0
Bank Sta=636.5,879.4
XS Rating Curve= 0 ,0
Exp/Cntr=0.3,0.1

Type RM Length L Ch R = 1 ,10891.1 ,729.5,718.9,708.3
XS GIS Cut Line= 3
     1798324.087      214682.489     1798296.048      214000.566
     1798268.008      213318.642
#Sta/Elev= 30
       0 1536.75    29.2 1527.25    58.5 1514.88      78 1505.71   146.2 1471.91
   243.8 1419.53   263.2 1410.54   302.2 1393.96  351.95 1374.33   370.5 1368.59
   380.2 1367.11     3931366.485  432.751364.778  486.071362.275  509.191361.126
   536.2 1360.53     780 1360.72   789.8 1362.06   809.2 1371.59   828.8    1380
   877.5 1396.26   916.5 1406.54   965.2 1420.57  1023.8 1436.15  1101.8 1459.08
    1170 1480.59    1209 1491.68  1316.2  1519.4    1326 1522.47    1365 1537.19
#Mann= 8 ,-1 , 0
       0     .12       0  351.95    .016       0     393     .12       0
  432.75     .06       0  486.07     .12       0  509.19     .06       0
   536.2    .045       0     780     .12       0
Bank Sta=536.2,780
XS Rating Curve= 0 ,0
Exp/Cntr=0.3,0.1

Type RM Length L Ch R = 1 ,10172.1 ,744.3,737,729.9
XS GIS Cut Line= 2
      1799326.91      214464.725     1798698.438      213339.725
#Sta/Elev= 30
       0 1586.69    39.4 1568.98    88.5 1541.59   137.7  1512.2   186.9 1484.96
   216.4 1469.58   255.8  1451.9   275.4 1442.01   383.6 1381.68   393.5 1378.45
   403.3 1376.92   452.5 1373.89  491.631369.959  552.951362.587  568.631360.991
   580.4 1360.54   590.2 1360.53   796.8 1360.78  799.151360.938   806.6 1361.44
   816.5 1363.84     846 1377.78   855.8 1380.23   885.3 1381.06   895.2 1382.77
  1111.6  1434.5  1170.6 1451.14    1210 1458.68  1249.3 1470.93  1288.6 1487.32
#Mann= 7 ,-1 , 0
       0     .12       0  491.63    .016       0  552.95     .12       0
  568.63     .04       0   580.4    .045       0   796.8     .04       0
  799.15     .12       0
Bank Sta=580.4,796.8
XS Rating Curve= 0 ,0
Exp/Cntr=0.3,0.1

Type RM Length L Ch R = 1 ,9435.1  ,721.2,724.8,728
XS GIS Cut Line= 2
     1799854.688      213669.586      1799233.16      213100.142
#Sta/Elev= 30
       0 1463.98    29.4 1456.76    39.2 1453.85      49  1450.2    58.8  1445.8
      98 1426.94   117.6 1418.37   137.2  1411.1   166.6 1402.63   215.6 1391.95
   284.2 1380.22  384.911367.319   401.9 1364.18   411.7 1361.16   421.5 1358.46
   431.3 1357.72   509.7 1358.04   578.3 1359.54  595.841359.906   607.7 1360.44
   617.5 1361.79  627.391364.063   646.9 1369.18   666.5 1375.63   676.3 1378.14
   705.7 1380.12   715.5 1382.55   725.3 1386.35   744.9 1395.62     843 1447.04
#Mann= 6 ,-1 , 0
       0     .12       0  384.91    .016       0   411.7    .045       0
   578.3     .04       0  595.84     .08       0  627.39     .12       0
Bank Sta=411.7,578.3
XS Rating Curve= 0 ,0
Exp/Cntr=0.3,0.1

Type RM Length L Ch R = 1 ,8710.4  ,615.1,639.7,664.2
XS GIS Cut Line= 2
     1800257.466       213145.28     1799753.993      212523.753
#Sta/Elev= 30
       0 1446.43    5.181443.592    29.3    1432   73.231415.606  110.081401.539
  198.071366.528   204.8  1364.1   214.6    1362  243.29  1357.3   259.71355.927
   263.4 1355.87   429.2  1356.5     439 1358.44  448.011362.007   468.2 1370.21
   507.2 1378.67   526.7 1379.67   565.8 1379.75   585.3 1382.51   604.8 1388.42
     634 1402.46   643.8 1405.34   663.3 1408.28   682.8 1417.14   692.6 1420.33
   702.3 1421.45   712.1 1421.44   731.6 1419.66   770.6 1418.47   799.9 1416.26
#Mann= 9 ,-1 , 0
       0    .016       0    5.18     .12       0   73.23    .016       0
  110.08     .12       0  198.07    .016       0  243.29     .04       0
   259.7    .045       0   429.2     .08       0  448.01     .12       0
Bank Sta=259.7,429.2
XS Rating Curve= 0 ,0
Exp/Cntr=0.3,0.1

Type RM Length L Ch R = 1 ,8070.7  ,464.8,489.1,513.5
XS GIS Cut Line= 2
     1800438.021      213023.753     1800778.299      212221.669
#Sta/Elev= 30
       0 1426.11    39.2 1422.81    58.7 1422.34   67.091421.758    78.3 1420.02
    88.1 1417.57   107.7 1411.29   146.8  1397.7   156.6 1394.56  172.481390.299
   205.6 1381.85  237.111371.948  252.531367.231  301.751356.961   313.3 1355.49
   323.1 1355.23   499.3 1355.32   509.1 1357.03   528.6 1363.96     558 1371.98
   567.8 1373.76   587.4  1374.6   597.2 1375.75     607 1379.02   616.8 1383.87
   685.3 1421.87   773.4 1469.79   802.8  1485.3   822.3 1494.54   871.3 1515.69
#Mann= 8 ,-1 , 0
       0     .12       0   67.09     .06       0  172.48     .12       0
  237.11     .06       0  252.53    .016       0  301.75     .04       0
   323.1    .045       0   499.3     .12       0
Bank Sta=323.1,499.3
XS Rating Curve= 0 ,0
Exp/Cntr=0.3,0.1

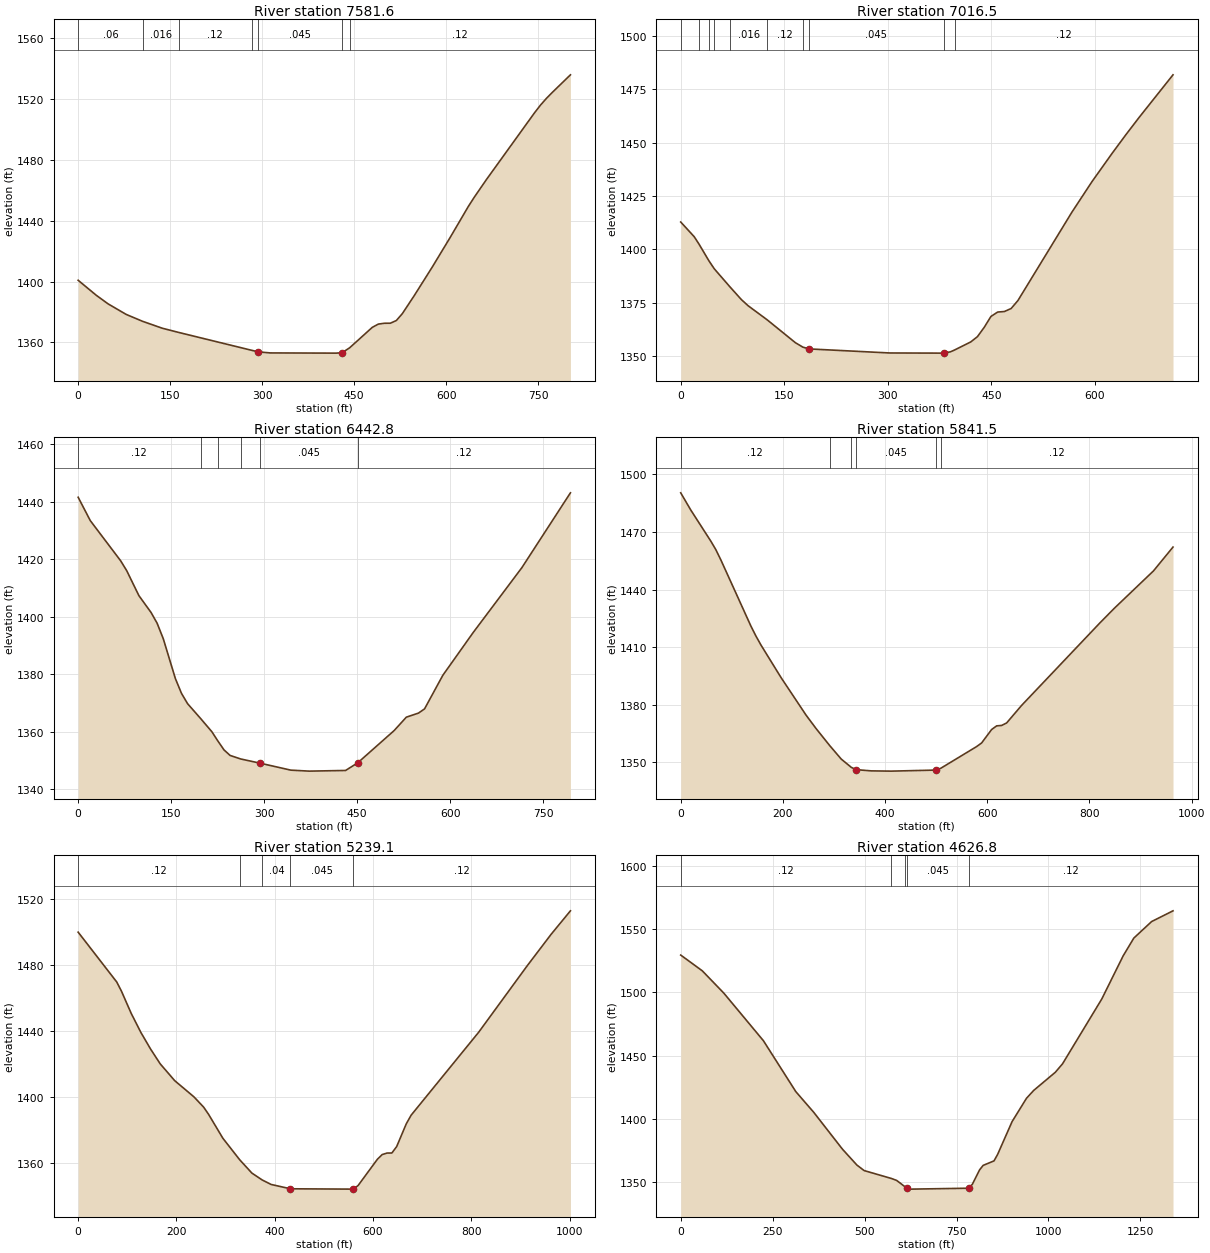
Type RM Length L Ch R = 1 ,7581.6  ,551.2,565.1,579
XS GIS Cut Line= 2
     1800524.827       213051.53     1801323.438      212971.669
#Sta/Elev= 30
       0 1400.87    29.4 1391.04    48.9 1385.32    78.3  1378.4   105.11373.849
     137 1369.33  164.381366.492  282.941354.776   293.6 1353.76   313.2 1353.05
   420.9 1352.92   430.7 1353.27  442.56 1356.41   479.6  1369.9   489.4 1372.02
   499.2 1372.58     509 1372.61   518.8 1374.38   528.5 1378.88   548.1 1390.86
   577.5 1409.68   606.8 1429.24   636.2  1449.5     646 1455.64   665.6 1467.13
   743.9    1511   753.7 1516.11   763.4 1520.56   773.2 1524.57   802.6 1536.08
#Mann= 7 ,-1 , 0
       0     .06       0   105.1    .016       0  164.38     .12       0
  282.94     .08       0   293.6    .045       0   430.7     .04       0
  442.56     .12       0
Bank Sta=293.6,430.7
XS Rating Curve= 0 ,0
Exp/Cntr=0.3,0.1

Type RM Length L Ch R = 1 ,7016.5  ,583.3,573.7,564
XS GIS Cut Line= 2
     1800392.882      213374.447     1801017.882      213718.197
#Sta/Elev= 30
       0 1412.76    19.5 1405.89   26.471402.419   40.621394.696   48.59 1390.85
   71.311382.371    87.9  1376.4    97.7 1373.51  125.271366.921   166.1 1356.21
  176.72 1354.16   185.6 1353.29   302.9 1351.38   381.1 1351.31   390.8 1351.92
  396.991352.804   420.2 1356.55   429.9 1359.02   439.7 1363.37   449.5  1368.5
   459.2 1370.56     469 1370.81   478.8 1372.23   488.6 1375.96   566.7 1417.31
     596 1431.73   625.4 1445.09   644.9 1453.62   664.4 1461.86   713.3 1481.74
#Mann= 10 ,-1 , 0
       0     .12       0   26.47     .06       0   40.62     .12       0
   48.59     .06       0   71.31    .016       0  125.27     .12       0
  176.72     .08       0   185.6    .045       0   381.1     .04       0
  396.99     .12       0
Bank Sta=185.6,381.1
XS Rating Curve= 0 ,0
Exp/Cntr=0.3,0.1

Type RM Length L Ch R = 1 ,6442.8  ,619,601.3,583.4
XS GIS Cut Line= 2
     1800066.493      213992.503      1800858.16      214055.003
#Sta/Elev= 30
       0 1441.54    19.6  1433.4    68.6 1419.42    78.4 1415.96      98  1407.3
   117.6 1401.44   127.4  1397.7   137.3 1392.31   156.9  1378.4   166.7 1373.29
   176.5 1369.71   197.41364.573   215.7 1359.94   225.2 1356.78   235.3 1353.61
   245.1 1351.69  262.19 1350.46   294.1 1348.97   343.1 1346.57   372.6 1346.23
   431.4 1346.46     451 1349.12   509.8 1360.36   529.4 1365.01     549 1366.43
   558.8  1367.9   588.2 1379.56   637.3 1394.49   715.7 1417.02   794.1 1443.08
#Mann= 6 ,-1 , 0
       0     .12       0   197.4    .016       0   225.2     .12       0
  262.19     .04       0   294.1    .045       0     451     .12       0
Bank Sta=294.1,451
XS Rating Curve= 0 ,0
Exp/Cntr=0.3,0.1

Type RM Length L Ch R = 1 ,5841.5  ,610.1,602.4,594.7
XS GIS Cut Line= 3
     1800208.855      214860.558     1800708.855      214433.475
     1800979.688      214291.114
#Sta/Elev= 30
       0 1490.41    19.6 1481.48    58.9 1465.23    68.7  1460.8    78.5 1455.47
   137.4 1420.94   147.2 1415.76     157  1411.1   196.3 1394.14   245.4 1374.51
     265 1367.51  291.871358.579   314.1 1351.65  333.921347.303   343.5 1346.11
     373 1345.48   412.2 1345.35   500.5  1345.9  509.411346.908   579.1 1358.14
   588.9 1360.03   608.5 1367.03   618.3 1368.94   628.1 1369.16   637.9 1370.47
   667.1 1379.58   820.1 1422.52   848.8 1430.27   925.3 1449.72   963.5 1462.14
#Mann= 6 ,-1 , 0
       0     .12       0  291.87    .016       0  333.92     .04       0
   343.5    .045       0   500.5     .04       0  509.41     .12       0
Bank Sta=343.5,500.5
XS Rating Curve= 0 ,0
Exp/Cntr=0.3,0.1

Type RM Length L Ch R = 1 ,5239.1  ,612.9,612.4,611.9
XS GIS Cut Line= 2
     1800781.771      215343.197     1801281.771      214475.142
#Sta/Elev= 30
       0 1499.74    78.6 1469.57    88.4 1463.88     108 1450.59   127.7 1439.07
   147.3  1429.1     167  1420.1   196.4 1409.96   235.7 1400.12   255.4 1393.91
   265.2 1389.67   294.6 1375.06  328.761362.095   353.6 1354.03  374.451349.888
   392.8 1347.15   432.1 1344.54   559.8 1344.34   569.6 1346.48   608.9 1362.38
   618.7 1365.24   628.6 1366.16   638.4 1366.18   648.2 1370.08   667.8 1383.88
   677.7 1389.09   815.2 1439.27   913.4 1479.24   962.5 1498.44  1001.8 1512.64
#Mann= 5 ,-1 , 0
       0     .12       0  328.76    .016       0  374.45     .04       0
   432.1    .045       0   559.8     .12       0
Bank Sta=432.1,559.8
XS Rating Curve= 0 ,0
Exp/Cntr=0.3,0.1

Type RM Length L Ch R = 1 ,4626.8  ,487.7,497.8,507.6
XS GIS Cut Line= 4
     1801107.726      215677.832     1801463.629      215387.034
     1801745.747      214870.541     1801806.077      214586.253
#Sta/Elev= 30
       0 1529.45    58.7 1516.99   117.3 1499.33   224.9 1461.72   312.9 1421.52
   361.8  1405.1     440 1375.92   479.2  1363.4   498.8 1359.07  572.771352.833
   587.1 1351.29  610.681346.108   616.5 1344.98   626.4  1344.4   783.3 1345.12
   793.1 1348.27   812.7 1359.62   822.5 1363.18   851.9 1366.72   861.8 1371.86
     901 1397.73   940.2  1416.2   959.8 1422.42  1018.7 1436.79  1038.3 1443.48
    1145 1494.72  1203.1  1528.8  1232.2  1542.9  1280.6 1555.96  1338.7 1564.43
#Mann= 5 ,-1 , 0
       0     .12       0  572.77    .016       0  610.68     .04       0
   616.5    .045       0   783.3     .12       0
Bank Sta=616.5,783.3
XS Rating Curve= 0 ,0
Exp/Cntr=0.3,0.1

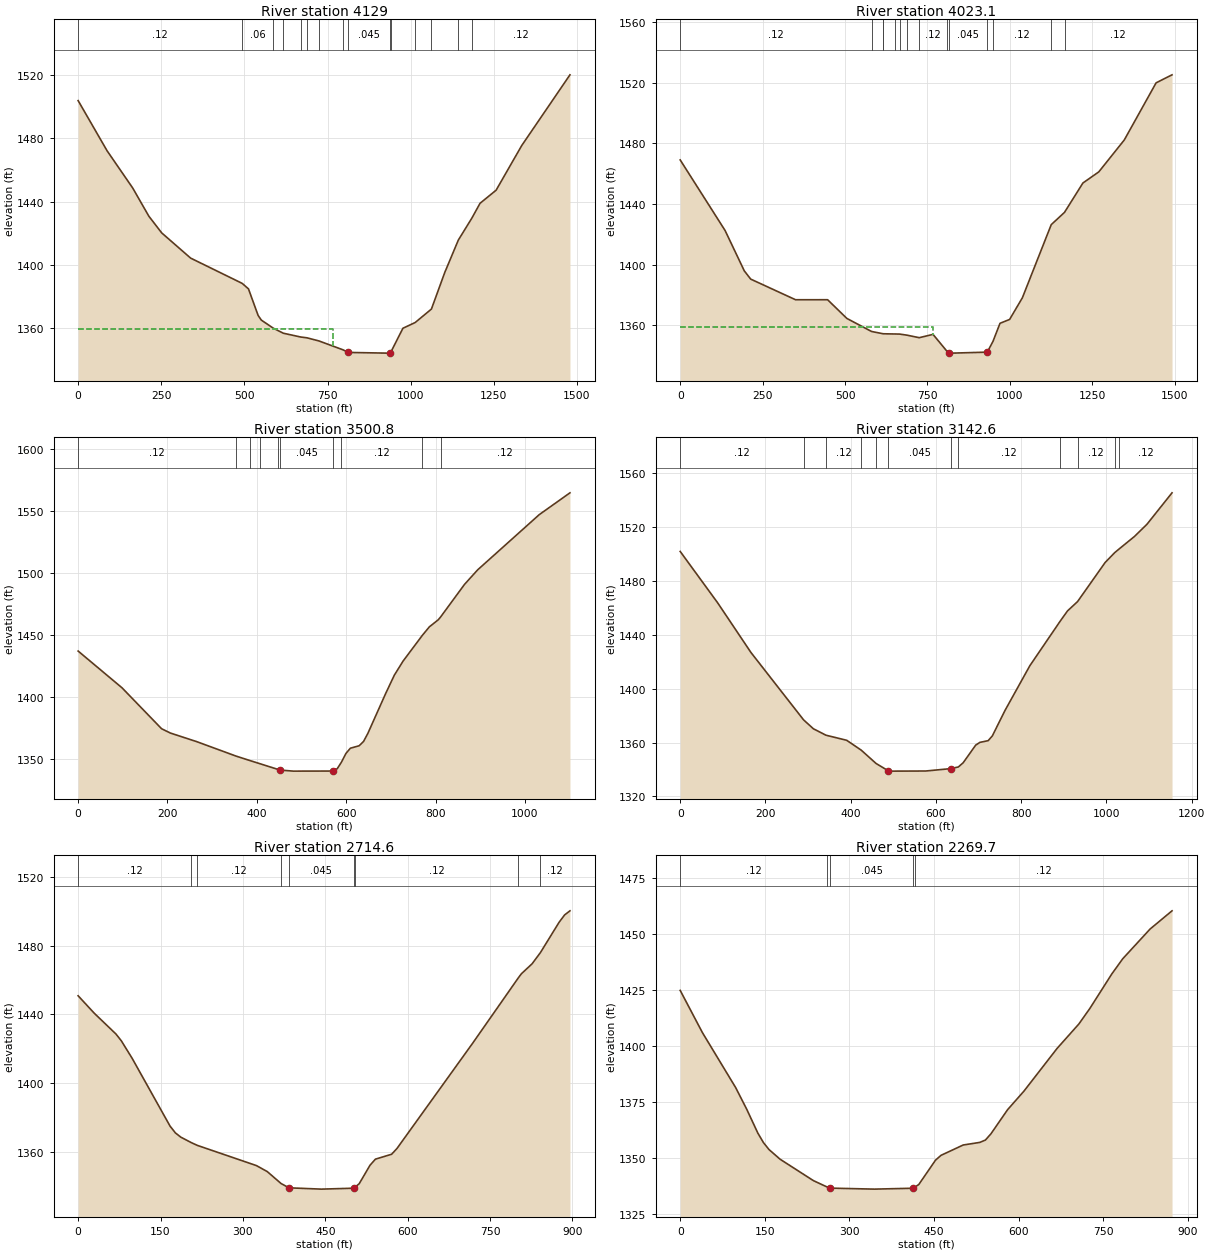
Type RM Length L Ch R = 1 ,4129    ,105.9,105.9,105.9
XS GIS Cut Line= 4
     1801200.087      215697.624     1801710.504      215653.353
     1802155.816      215327.832     1802562.066      215241.895
#Sta/Elev= 30
       0 1503.98      87 1472.23   164.3 1448.59   212.7 1430.79   251.3 1420.23
   338.3 1404.26   493.31388.265   512.3 1384.79   541.4 1367.92     551    1365
  587.091359.862  617.181356.694  669.471354.286  688.391353.774  724.541351.789
  796.851346.167   812.3 1344.53   928.5 1344.09   938.1 1344.35  941.461345.109
   976.8 1359.84 1013.771363.483 1062.531371.983  1102.6 1395.12 1143.511415.681
 1183.961429.495  1208.8 1438.96  1257.1 1447.25  1334.3 1475.58  1479.2  1520.3
#Mann= 15 ,-1 , 0
       0     .12       0   493.3     .06       0  587.09     .12       0
  617.18     .06       0  669.47     .08       0  688.39    .016       0
  724.54     .12       0  796.85     .04       0   812.3    .045       0
   938.1     .04       0  941.46     .08       0 1013.77    .016       0
 1062.53     .12       0 1143.51    .016       0 1183.96     .12       0
#XS Ineff= 2 , 0
           767.8 1359.12
Permanent Ineff=
       F       F
Bank Sta=812.3,938.1
XS Rating Curve= 0 ,0
Exp/Cntr=0.3,0.1

Type RM Length L Ch R = 1 ,4023.1  ,516.5,522.3,528.1
XS GIS Cut Line= 4
     1801257.379      215770.541     1801780.816      215731.478
     1802226.129      215405.957     1802632.379       215320.02
#Sta/Elev= 30
       0 1469.03   136.1 1422.48   194.4 1395.84   213.8  1390.4   349.9 1376.78
   447.1 1376.79   505.4 1364.47  580.331355.851  614.631354.372  616.481354.324
  652.631354.184  665.85 1354.12  688.791353.373  724.941351.746   766.8 1353.93
  807.88  1343.1   815.2 1341.84   824.9 1341.56   931.3 1342.21  948.57 1349.27
     970 1361.24   999.1 1363.78  1037.8 1378.07 1125.361426.336 1165.581434.428
  1221.4  1453.8  1269.6 1461.15  1346.9  1482.2  1443.4 1519.89  1491.7 1525.18
#Mann= 14 ,-1 , 0
       0     .12       0  580.33     .08       0  614.63     .12       0
  616.48    .016       0  652.63     .06       0  665.85    .016       0
  688.79     .06       0  724.94     .12       0  807.88     .04       0
   815.2    .045       0   931.3     .04       0  948.57     .12       0
 1125.36    .016       0 1165.58     .12       0
#XS Ineff= 2 , 0
           767.8  1358.7
Permanent Ineff=
       F       F
Bank Sta=815.2,931.3
XS Rating Curve= 0 ,0
Exp/Cntr=0.3,0.1

Type RM Length L Ch R = 1 ,3500.8  ,361.2,358.2,355.1
XS GIS Cut Line= 2
     1801769.184      216206.478      1802793.49      215802.832
#Sta/Elev= 30
       0  1436.8    98.3 1407.16   186.8  1374.2   206.4 1370.74   265.4  1363.8
  353.111352.198  384.661348.541   407.21345.985  447.751341.362   452.2 1340.89
   481.7 1340.03   570.1  1340.1     580 1341.98  589.391347.231   599.6 1354.34
   609.5  1358.5   629.1 1360.48     639 1363.97   648.8 1370.61   688.1  1402.3
   707.8 1417.34   727.4  1428.7  770.471449.415   786.4 1456.36   806.1 1461.98
  811.241464.172     865 1490.54   894.5 1502.28  1032.2 1546.72    1101 1564.32
#Mann= 10 ,-1 , 0
       0     .12       0  353.11     .06       0  384.66    .016       0
   407.2     .12       0  447.75     .08       0   452.2    .045       0
   570.1     .04       0  589.39     .12       0  770.47    .016       0
  811.24     .12       0
Bank Sta=452.2,570.1
XS Rating Curve= 0 ,0
Exp/Cntr=0.3,0.1

Type RM Length L Ch R = 1 ,3142.6  ,435.8,428,420.1
XS GIS Cut Line= 3
     1801879.427      216630.957     1802569.532      216244.673
     1802808.247      215971.235
#Sta/Elev= 30
       0 1502.03    87.9 1463.82     166 1426.91  289.451376.828   312.4 1370.23
  341.941365.437   390.6 1361.65  424.661354.326  459.531344.411   488.2 1338.98
     498 1338.73   576.1 1338.82   634.6 1340.59  652.571341.825   663.9 1344.98
   693.2 1358.05     703 1360.09   722.5 1361.38   732.3 1364.93   761.6 1383.61
   820.3  1417.1  891.561450.257   908.6 1457.81   932.21464.755   996.9 1493.81
 1019.251501.108 1030.051503.957  1065.6 1513.13    1095 1522.22  1153.8 1545.59
#Mann= 12 ,-1 , 0
       0     .12       0  289.45     .06       0  341.94     .12       0
  424.66    .016       0  459.53     .12       0   488.2    .045       0
   634.6     .04       0  652.57     .12       0  891.56    .016       0
   932.2     .12       0 1019.25     .06       0 1030.05     .12       0
Bank Sta=488.2,634.6
XS Rating Curve= 0 ,0
Exp/Cntr=0.3,0.1

Type RM Length L Ch R = 1 ,2714.6  ,444.1,444.9,445.7
XS GIS Cut Line= 2
      1802391.58       216986.86     1802977.518      216309.777
#Sta/Elev= 30
       0 1450.83    29.5 1440.64    68.9 1428.59    78.7 1424.62    98.4 1414.45
   167.3 1375.09   177.1 1371.11     187 1368.64  205.811365.494  216.931363.874
   324.7  1352.1   344.4 1348.61  369.481341.691   383.8 1339.19   442.8 1338.43
   501.8 1338.97  504.291339.624   511.7 1341.57   531.3 1352.27   541.2 1355.85
   570.7  1358.7   580.5 1362.07   718.3 1423.27  801.381461.236   806.9  1463.6
   826.5 1469.43  841.571475.908   875.7 1493.59   885.6  1497.8   895.4 1500.21
#Mann= 9 ,-1 , 0
       0     .12       0  205.81    .016       0  216.93     .12       0
  369.48     .04       0   383.8    .045       0   501.8     .04       0
  504.29     .12       0  801.38    .016       0  841.57     .12       0
Bank Sta=383.8,501.8
XS Rating Curve= 0 ,0
Exp/Cntr=0.3,0.1

Type RM Length L Ch R = 1 ,2269.7  ,438.1,432.9,427.6
XS GIS Cut Line= 3
     1802760.504      217221.235     1803155.469      216795.888
     1803133.768      216505.089
#Sta/Elev= 30
       0 1424.96    39.4 1406.09    98.4 1381.49   118.1 1371.76   137.7 1361.16
   147.6 1356.93   157.4 1353.84   177.1  1349.5   236.1 1339.94  260.531337.072
   265.6 1336.58   344.3 1336.13   413.2 1336.53  416.881337.154     423 1338.19
   452.6 1349.05   462.4 1351.23   501.7 1355.85   531.3 1357.02   541.1 1358.07
   550.9 1360.84   580.4 1371.62   609.6 1379.98   667.9 1398.93   706.8 1409.94
   726.2 1416.85   765.1 1432.26   784.6  1439.1   833.2 1452.41     872 1460.53
#Mann= 5 ,-1 , 0
       0     .12       0  260.53     .04       0   265.6    .045       0
   413.2     .04       0  416.88     .12       0
Bank Sta=265.6,413.2
XS Rating Curve= 0 ,0
Exp/Cntr=0.3,0.1

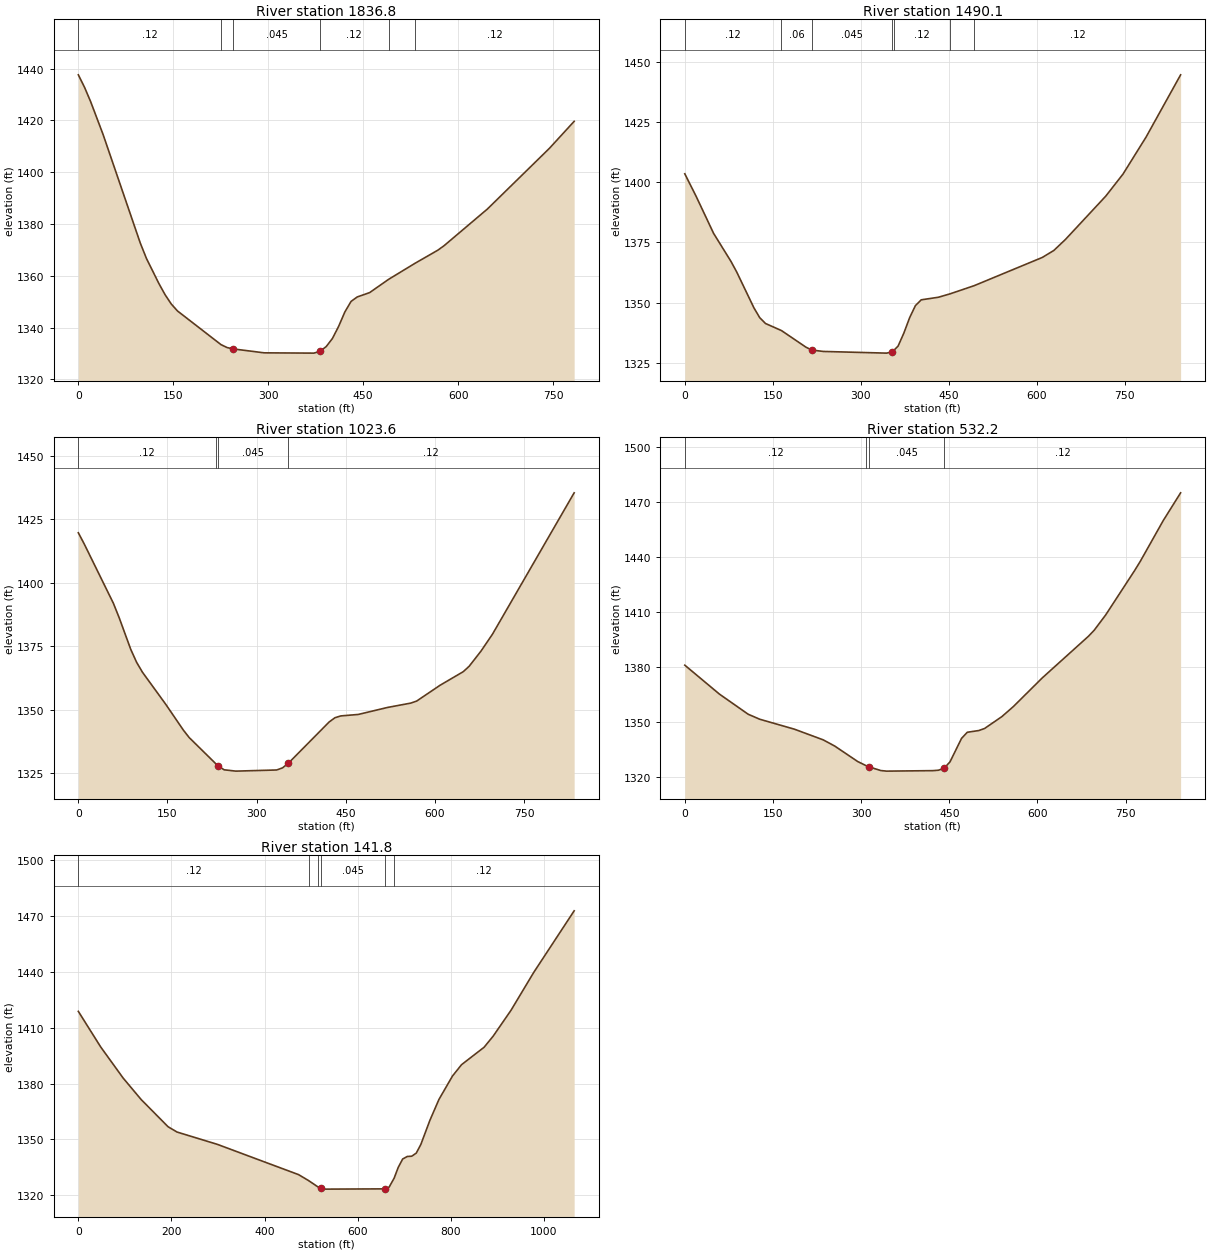
Type RM Length L Ch R = 1 ,1836.8  ,346.9,346.7,346.6
XS GIS Cut Line= 2
     1803218.837      217449.534     1803605.122       216768.11
#Sta/Elev= 30
       0 1437.63     9.8 1432.81    19.6 1427.18    39.2 1414.52    97.9 1372.62
   107.7 1366.64   127.3    1357   137.1 1352.67   146.9 1349.07   156.7  1346.4
   225.31333.418     235 1332.27   244.8 1331.74   293.7 1330.23   372.1 1330.12
   381.9 1330.82   391.6 1332.65   401.4 1335.77   411.2 1340.45     421 1345.99
   430.8 1350.08   440.6 1351.82   460.2  1353.5  490.131358.618  531.371364.746
   567.9 1369.88   577.7  1371.6   646.2 1385.78   744.1 1409.21   783.3 1419.66
#Mann= 6 ,-1 , 0
       0     .12       0   225.3     .04       0   244.8    .045       0
   381.9     .12       0  490.13    .016       0  531.37     .12       0
Bank Sta=244.8,381.9
XS Rating Curve= 0 ,0
Exp/Cntr=0.3,0.1

Type RM Length L Ch R = 1 ,1490.1  ,466.6,466.5,466.4
XS GIS Cut Line= 2
     1803520.052      217624.881     1803932.379      216887.034
#Sta/Elev= 30
       0 1403.48    19.7 1393.94    49.1 1378.74    78.6 1367.15    88.5  1362.7
   117.9 1347.78   127.8 1343.71   137.6 1341.31  164.751338.386   206.4  1331.5
   216.2 1330.31   235.9 1329.71     344 1329.01   353.8 1329.54     3561330.079
   363.6 1331.94   373.5 1337.38   383.3 1343.74   393.1 1348.73     403 1351.14
   432.4 1352.22  452.171353.625  493.421357.034   609.4 1368.74     629 1371.63
   648.7 1376.17   717.5 1394.18     747 1403.37   786.3 1418.73   845.2 1444.58
#Mann= 7 ,-1 , 0
       0     .12       0  164.75     .06       0   216.2    .045       0
   353.8     .04       0     356     .12       0  452.17    .016       0
  493.42     .12       0
Bank Sta=216.2,353.8
XS Rating Curve= 0 ,0
Exp/Cntr=0.3,0.1

Type RM Length L Ch R = 1 ,1023.6  ,493.4,491.4,489.4
XS GIS Cut Line= 2
      1803908.42      217885.124     1804312.587      217155.263
#Sta/Elev= 30
       0 1419.61     9.8 1415.26    58.9  1391.9    68.7 1386.19    88.3 1373.66
    98.2 1368.56     108 1364.69   147.2 1352.06   176.7 1341.95   186.5 1339.01
  231.441328.674   235.6 1327.77   245.4 1326.31     265 1325.79   333.7 1326.24
   343.5 1327.06   353.4  1328.9   422.1 1345.15   431.9 1346.82   441.7 1347.52
   471.1  1348.1   520.2 1350.85   559.5 1352.57   569.3 1353.37   608.5 1359.56
   647.8 1364.95   657.6 1367.06   677.2 1372.92   696.9  1379.7   834.3 1435.33
#Mann= 4 ,-1 , 0
       0     .12       0  231.44     .04       0   235.6    .045       0
   353.4     .12       0
Bank Sta=235.6,353.4
XS Rating Curve= 0 ,0
Exp/Cntr=0.3,0.1

Type RM Length L Ch R = 1 ,532.2   ,390.7,390.4,390.1
XS GIS Cut Line= 2
     1804366.407       218071.93     1804704.948       217299.36
#Sta/Elev= 30
       0 1381.11    58.8 1365.36   107.9 1354.33   127.5 1351.62   186.4  1346.2
   235.4 1340.38     255    1337   294.2 1328.54  308.211326.333   313.9 1325.58
   333.5 1323.62   343.3 1323.31   421.7 1323.57   431.6 1323.81   441.4 1324.94
   451.2 1328.39   470.8 1341.17   480.6 1344.51   500.2 1345.45     510 1346.57
   539.4 1353.05   559.1 1358.57   608.1 1374.16   686.6 1396.85   696.4 1400.14
     716 1408.51     765 1432.61   774.8 1437.71   814.1 1460.09   843.5 1475.13
#Mann= 4 ,-1 , 0
       0     .12       0  308.21     .04       0   313.9    .045       0
   441.4     .12       0
Bank Sta=313.9,441.4
XS Rating Curve= 0 ,0
Exp/Cntr=0.3,0.1

Type RM Length L Ch R = 1 ,141.8   ,141.3,141.8,142.2
XS GIS Cut Line= 4
     1804496.615      218281.999     1804800.434      218060.645
     1804974.045      217648.319     1804934.983      217409.603
#Sta/Elev= 30
       0 1418.78    48.2 1399.62    96.4 1382.93   134.9 1371.46   192.8 1356.83
     212 1353.99   298.8 1347.36   473.2 1331.11  494.671327.917  514.491324.572
   521.8 1323.69   531.5 1323.33     658 1323.47   667.7 1324.41  678.561329.267
   687.1 1334.91   696.8 1339.51   706.6 1340.85   716.3 1341.02     726 1342.68
   735.8 1347.31   755.2 1360.22   774.7 1371.48   803.8 1384.06   823.3 1390.16
   871.7 1399.51     891 1405.41   929.7 1419.42   978.1  1439.6  1065.2 1472.77
#Mann= 6 ,-1 , 0
       0     .12       0  494.67     .06       0  514.49     .04       0
   521.8    .045       0     658     .04       0  678.56     .12       0
Bank Sta=521.8,658
XS Rating Curve= 0 ,0
Exp/Cntr=0.3,0.1

Chan Stop Cuts=-1
Use User Specified Reach Order=0
Composite Channel Slope=5